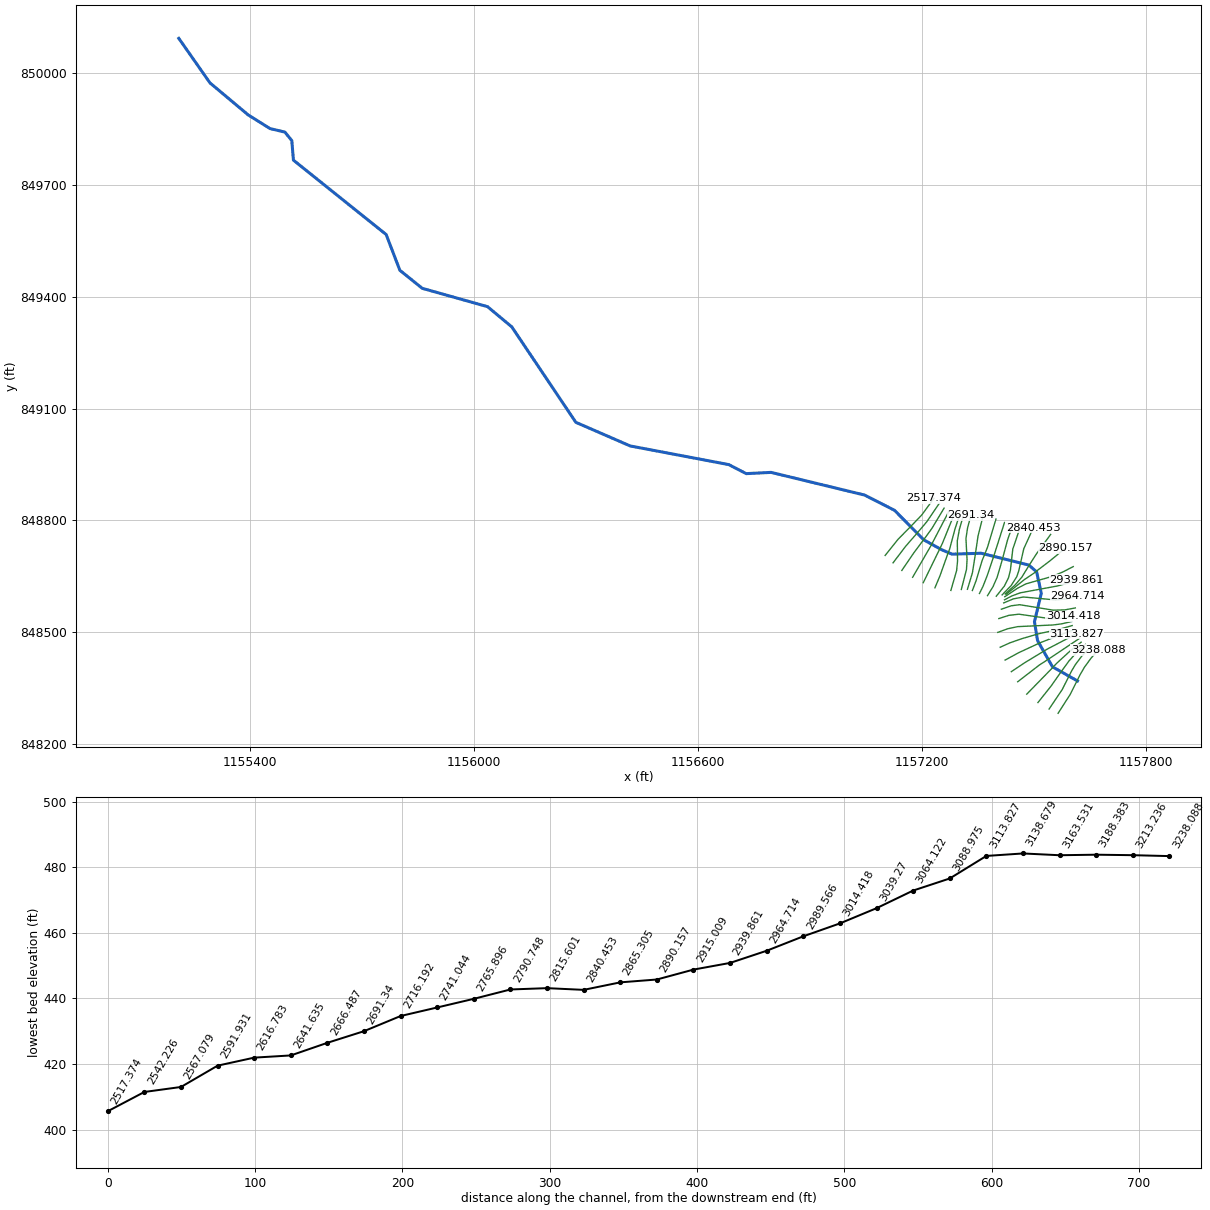
--- 167_ras.prj (project) ---

Proj Title=167
Current Plan=p01
Default Exp/Contr=0.3,0.1
English Units
Geom File=g01
Flow File=f01
Plan File=p01
Y Axis Title=Elevation
X Axis Title(PF)=Main Channel Distance
X Axis Title(XS)=Station
BEGIN DESCRIPTION:
RFD model 167 exported to HEC-RAS
END DESCRIPTION:

--- 167_ras.p01 (plan) ---

Plan Title=Plan 01
Program Version=4.10
Short Identifier=Plan 01
Geom File=g01
Flow File=f01
Subcritical Flow
Calc Critical at every XS
Secant Critical Depth

--- 167_ras.f01 (steady flow) ---

Flow Title=Flow 01
Program Version=5.01
Number of Profiles= 5
Profile Names=10yr,25yr,50yr,100yr,500yr
River Rch & RM=167,95,3238.088
  115.54   205.2  291.48  394.52   696.7
River Rch & RM=167,95,3088.975
   119.9  213.12  302.96  410.41   726.4
River Rch & RM=167,95,2915.009
  147.84  263.98  376.92  513.03  919.65
River Rch & RM=167,95,2765.896
  154.03  275.27  393.38  535.93  963.11
River Rch & RM=167,95,2666.487
  158.97   284.3  406.56  554.28  997.99
River Rch & RM=167,95,2567.079
  160.82  287.69   411.5  561.16  1011.1
River Rch & RM=167,95,2442.818
  165.76  296.72  424.69  579.54 1046.13
River Rch & RM=167,95,2343.409
  170.69  305.74  437.88  597.94 1081.26
River Rch & RM=167,95,2268.852
  179.32  321.54  460.97  630.17 1142.97
River Rch & RM=167,95,2169.443
  181.16  324.92  465.92  637.09 1156.23
River Rch & RM=167,95,2070.035
  185.47  332.81  477.47  653.23 1187.22
River Rch & RM=167,95,1970.626
  207.56  373.38  536.95  736.48  1347.7
River Rch & RM=167,95,1871.217
  226.53  408.29  588.23  808.41 1487.22
River Rch & RM=167,95,1771.808
  241.19   435.3  627.97  864.26 1596.02
River Rch & RM=167,95,  1672.4
  246.07  444.31  641.23   882.9 1632.43
River Rch & RM=167,95,1572.991
   254.6  460.05  664.43  915.56 1696.32
River Rch & RM=167,95, 1448.73
  267.99  484.79  700.91  966.95 1797.13
River Rch & RM=167,95,1325.812
  311.68   565.7  820.48 1135.78 2130.36
River Rch & RM=167,95,1227.747
  328.62  597.13  867.04 1201.67 2261.21
River Rch & RM=167,95,1118.291
  338.89  616.22  895.33 1241.74 2340.98
River Rch & RM=167,95, 980.654
  343.12  624.07  906.98 1258.25 2373.89
River Rch & RM=167,95,882.5886
  347.95  633.05  920.29 1277.13 2411.56
River Rch & RM=167,95,784.5232
  364.23  663.34  965.26 1340.92 2539.04
River Rch & RM=167,95,588.3924
  403.94  737.34 1075.27 1497.26 2852.95
River Rch & RM=167,95,480.5043
  415.96  759.76 1108.64 1544.74 2948.68
River Rch & RM=167,95,359.9682
  431.56  788.89 1152.04 1606.55 3073.53
River Rch & RM=167,95,294.1962
  435.75  796.73 1163.73 1623.21 3107.22
River Rch & RM=167,95,196.1308
  444.14  812.41 1187.11 1656.53 3174.69
River Rch & RM=167,95, 98.0654
  457.32  837.04 1223.86 1708.95 3280.96
Boundary for River Rch & Prof#=167,95,1
Up Type= 0
Dn Type= 2
Boundary for River Rch & Prof#=167,95,2
Up Type= 0
Dn Type= 2
Boundary for River Rch & Prof#=167,95,2
Up Type= 0
Dn Type= 2
Boundary for River Rch & Prof#=167,95,2
Up Type= 0
Dn Type= 2
Boundary for River Rch & Prof#=167,95,2
Up Type= 0
Dn Type= 2

--- 167_ras.g01 (geometry) ---

Geom Title=167
Program Version=4.10

River Reach=167,95
Reach XY= 30
 1157616.9164778 848369.917015941157549.89827526848407.861147761
1157509.98067603848478.0761557071157501.64734662848528.909474224
1157519.98067671848604.7427846641157507.48068205848662.242768034
1157486.64735538848680.5760965651157358.31406063848712.242757529
1157280.81408331848709.7427604941157253.31409171848721.409424528
 1157204.9807733848748.0760847031157126.64746529 848827.24273023
1157046.64748991848868.0760538281156795.81423199848928.909376383
 1156729.1475848 848925.576045961156682.48093253848949.742706835
1156418.31434482848999.7426996381156272.48105609849063.076018482
1156100.81444719849318.9092811791156035.81446785849373.075933725
1155860.81452066849422.2425908891155800.81453964849470.575911641
1155764.14788651 849566.409217731155515.58625299849765.725699097
1155511.21917361849818.1306515191155492.87744027849840.839464217
1155452.70031011849850.4470388291155394.18144652849887.130505517
1155291.99178931849972.7252611221155208.31473145850092.242411762

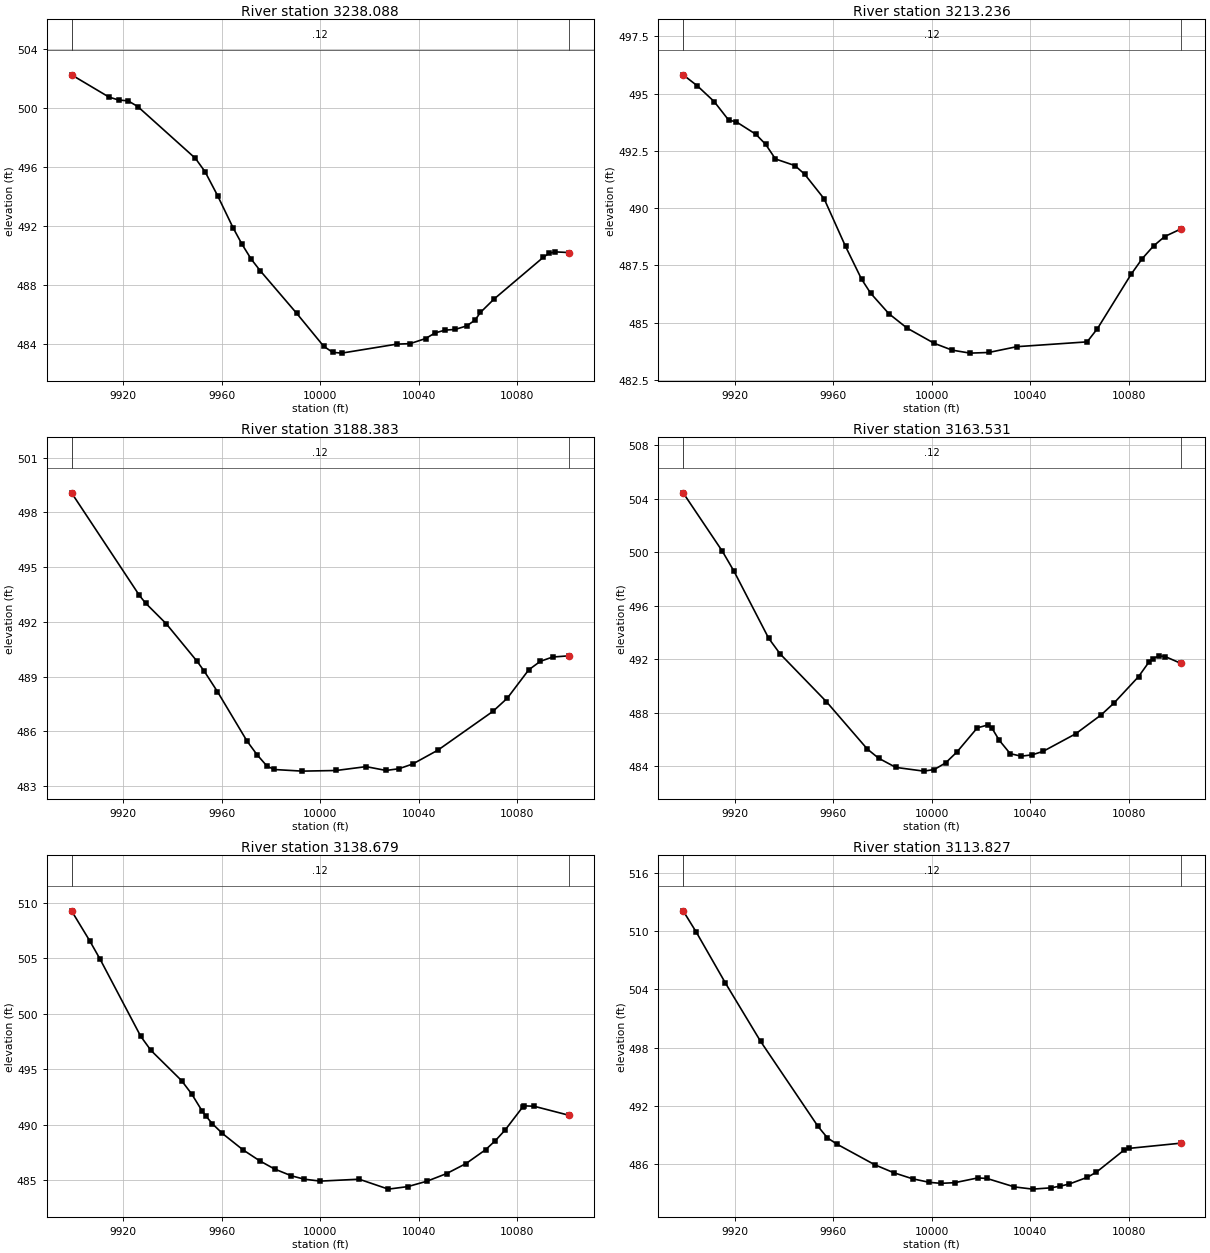
Type RM Length L Ch R = 1 ,3238.088,24.852200,24.852200,24.852200
XS GIS Cut Line= 6
1157565.01311301848283.3317886111157597.18176495848333.390658842
1157623.94966811848386.6862248261157635.68250312848406.853174717
1157654.12637371848432.0820454861157672.96364267848453.062819735
#Sta/Elev= 30
9899.037 502.2249914.236500.71779918.136500.52199922.036500.46029925.936500.0749
9949.335496.56859953.235 495.6689958.303494.05589964.581491.88179968.266490.7496
 9971.95489.75419975.634 488.9649990.372486.093510001.38483.855510005.03483.4419
10008.68483.387710031.07483.996510036.46484.028810042.77484.374910046.59484.7522
10050.65484.944810054.72484.989610059.45485.230410062.84485.622410065.01486.1399
10070.57487.050510090.47489.862910092.87490.146410095.38490.240610100.96 490.196
#Mann= 3 , 0 , 0
9899.037    0.12       09899.037    0.12       010100.96    0.12       0
#XS Ineff= 2 , 0
       0                               0
Bank Sta=9899.037,10100.96
Exp/Cntr=0.3,0.1

Type RM Length L Ch R = 1 ,3213.236,24.852200,24.852200,24.852200
XS GIS Cut Line= 6
1157540.79282435848294.5798484111157576.12292137848346.993143345
1157600.55304809 848395.550879891157611.34301403848413.809538617
1157628.47304295848436.4729996191157652.51102167848461.517626467
#Sta/Elev= 28
9899.051495.82199904.863495.3365 9911.66494.65269917.529493.84459920.689493.7653
9928.602493.22339932.559492.78459936.515492.14789944.429491.85819948.385491.4806
9956.298490.40539964.979488.32619971.461 486.9019975.152486.28559982.533485.3929
9989.914484.763210000.94484.097510008.22 483.799 10015.5483.667610023.07483.6959
10034.51483.949310063.03484.159510067.24484.741410080.88487.110910085.43487.7984
10089.98488.347210094.52488.759710100.95489.0834
#Mann= 3 , 0 , 0
9899.051    0.12       09899.051    0.12       010100.95    0.12       0
#XS Ineff= 2 , 0
       0                               0
Bank Sta=9899.051,10100.95
Exp/Cntr=0.3,0.1

Type RM Length L Ch R = 1 ,3188.383,24.852200,24.852200,24.852200
XS GIS Cut Line= 6
1157510.97588454848312.0016606951157545.97117822848355.908297239
1157572.31208372848393.4268044471157593.95936327848423.225834033
1157612.90801635848444.4010322221157638.41018011848467.961261369
#Sta/Elev= 24
9899.011499.07459926.574493.44799929.045 493.0319937.436 491.8999950.023489.8298
9952.893 489.2949958.269488.17139970.296485.45659974.305484.72049978.314484.0988
9981.246483.90489992.664483.815510006.44  483.85 10018.6484.061910026.71483.8527
10031.93483.946710037.51484.204510047.77 484.96710070.13487.095910075.93487.8131
10084.64489.369410089.33489.834210094.31490.070610100.97490.1378
#Mann= 3 , 0 , 0
9899.011    0.12       09899.011    0.12       010100.97    0.12       0
#XS Ineff= 2 , 0
       0                               0
Bank Sta=9899.011,10100.97
Exp/Cntr=0.3,0.1

Type RM Length L Ch R = 1 ,3163.531,24.852200,24.852200,24.852200
XS GIS Cut Line= 6
1157480.91770299848334.5051339491157550.79201483848406.017202636
1157551.93719215 848407.656888251157561.83779461848417.825714686
1157595.10001972848448.3223333681157626.73153987848473.864790329
#Sta/Elev= 30
9899.018 504.441 9914.97500.07049919.665498.58689933.748493.57759938.443   492.4
9957.221 488.8349973.784485.30569978.371484.61989985.388483.93059996.719483.6525
   10001483.772710005.59484.267310010.17485.078410018.46486.886210022.91487.1087
10024.43486.856910027.36485.959810031.81484.958710036.26484.768410040.71484.8692
10045.16485.127510058.42 486.44310068.72487.849110073.94 488.73410083.91490.7082
10088.13491.793910089.61492.052910092.35492.261610094.83492.203210100.98 491.713
#Mann= 3 , 0 , 0
9899.018    0.12       09899.018    0.12       010100.98    0.12       0
#XS Ineff= 2 , 0
       0                               0
Bank Sta=9899.018,10100.98
Exp/Cntr=0.3,0.1

Type RM Length L Ch R = 1 ,3138.679,24.852200,24.852200,24.852200
XS GIS Cut Line= 5
1157456.72730984848367.7439896391157514.13756748848412.146158222
1157537.10854941848427.0797488271157538.81999087848428.114624727
1157621.93338595848483.688884996
#Sta/Elev= 30
9899.024509.27889906.371506.59059910.653504.90469927.109497.97229931.256496.7007
9943.699493.97569947.847492.75769951.994491.25469953.554490.79219956.142490.0992
 9960.29489.20989968.585487.74349975.422486.74529981.441486.00829988.321 485.393
 9993.48485.091410000.04 484.916 10015.8485.088910027.64484.194110035.53484.4204
10043.42484.915310051.32485.596210059.21486.501510067.11487.742910071.05488.5537
   10075489.503710082.26491.611610082.89491.701510086.84 491.66410100.98490.8513
#Mann= 3 , 0 , 0
9899.024    0.12       09899.024    0.12       010100.98    0.12       0
#XS Ineff= 2 , 0
       0                               0
Bank Sta=9899.024,10100.98
Exp/Cntr=0.3,0.1

Type RM Length L Ch R = 1 ,3113.827,24.852200,24.852200,24.852200
XS GIS Cut Line= 6
1157439.65961334848394.8707875661157475.07720356848418.521786171
1157524.16265475848448.2866469361157525.86785729848449.331771004
1157535.02638582848454.8094775391157614.18350423848496.187208938
#Sta/Elev= 25
9899.007 512.1019904.325509.9173 9916.14504.68119930.463498.6571 9953.79489.8947
9957.627488.71369961.464488.07359976.811485.95229984.485485.13329992.159484.5053
    9999484.139110003.67484.036410009.31484.104510018.73484.597510022.43484.5354
10033.53483.668610040.94  483.4410048.34483.573310052.05483.745410055.75483.9622
10063.15484.658910066.85 485.19310077.96487.442210079.88487.631710100.99488.1707
#Mann= 3 , 0 , 0
9899.007    0.12       09899.007    0.12       010100.99    0.12       0
#XS Ineff= 2 , 0
       0                               0
Bank Sta=9899.007,10100.99
Exp/Cntr=0.3,0.1

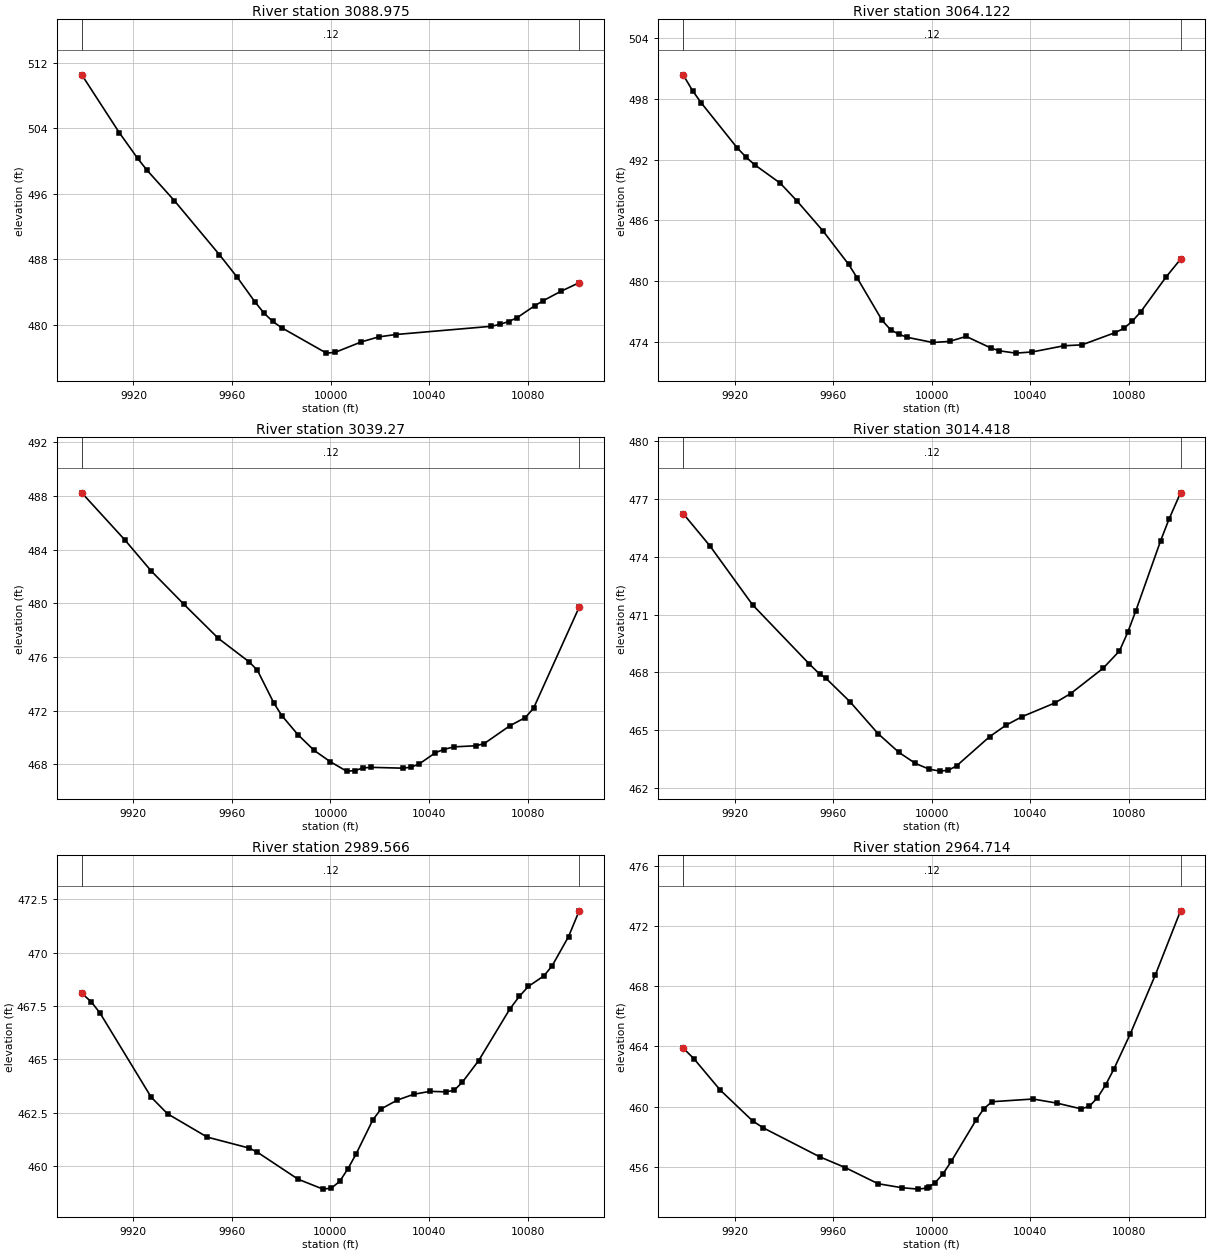
Type RM Length L Ch R = 1 ,3088.975,24.852200,24.852200,24.852200
XS GIS Cut Line= 6
1157422.94641156848425.7816993691157459.39771298848445.680688442
1157512.42627057 848470.279237931157514.24700355848471.106843764
1157518.37710021 848472.957829981157607.40552769848507.393517357
#Sta/Elev= 24
9899.015510.5057 9914.22503.46169921.695500.31439925.433498.89529936.647495.1442
9954.856488.5838 9962.09485.83259969.323482.8106 9972.94481.46319976.556480.4264
9980.173479.66039998.342476.563610001.86476.655710012.49477.930110019.53478.5414
10026.56478.834510065.26479.834910068.78480.070610072.29480.410510075.81480.8948
10082.85482.332110086.36482.9568 10093.4484.081310100.98 485.151
#Mann= 3 , 0 , 0
9899.015    0.12       09899.015    0.12       010100.98    0.12       0
#XS Ineff= 2 , 0
       0                               0
Bank Sta=9899.015,10100.98
Exp/Cntr=0.3,0.1

Type RM Length L Ch R = 1 ,3064.122,24.852200,24.852200,24.852200
XS GIS Cut Line= 6
 1157409.8598639848460.2888360591157435.73312851848472.055966502
1157468.63243632848483.4917489221157513.50359371848496.573152048
1157569.42983035848508.7907315441157602.79198789848518.405720307
#Sta/Elev= 30
9899.023500.38649902.832498.82819906.436497.59479920.853493.20369924.457492.2772
9928.039491.50269938.459489.67749945.406487.87679955.826484.9513 9966.18481.6642
9969.596480.35119979.843476.10859983.259475.19239986.674474.7394 9990.09474.4385
10000.35473.933110007.19474.038210013.94474.531410024.01473.383710027.37473.1119
10034.09472.880510040.81472.999110053.62473.608310060.95473.697310074.52474.9165
10077.94475.323910081.35476.024810084.77476.947710095.01480.374110100.98482.1635
#Mann= 3 , 0 , 0
9899.023    0.12       09899.023    0.12       010100.98    0.12       0
#XS Ineff= 2 , 0
       0                               0
Bank Sta=9899.023,10100.98
Exp/Cntr=0.3,0.1

Type RM Length L Ch R = 1 , 3039.27,24.852200,24.852200,24.852200
XS GIS Cut Line= 6
1157403.43345254848500.1466523061157429.95142201848509.774390769
1157456.53348194   848515.4714221157551.95953044848520.002690344
 1157574.5116494848523.0122103251157601.98243873848529.348649193
#Sta/Elev= 28
9899.053488.21989916.558484.70829927.265482.3957 9940.46 479.931 9954.45477.3904
9967.071475.62469970.366475.00139976.956472.5917 9980.25471.63569986.815470.2106
9993.381469.04589999.946468.202310006.51467.503910009.79 467.53110013.07467.7366
10016.36467.785610029.49467.723310032.77467.799710036.05468.041510042.62468.8781
 10045.9469.109110050.02 469.309 10059.1469.392610062.41469.555110072.77 470.876
10079.07471.490210082.44472.190510100.96 479.715
#Mann= 3 , 0 , 0
9899.053    0.12       09899.053    0.12       010100.96    0.12       0
#XS Ineff= 2 , 0
       0                               0
Bank Sta=9899.053,10100.96
Exp/Cntr=0.3,0.1

Type RM Length L Ch R = 1 ,3014.418,24.852200,24.852200,24.852200
XS GIS Cut Line= 6
1157406.28850645848537.1642823421157433.10687411848545.762984934
1157460.10242023848548.8655515041157546.09456633 848536.54647989
1157577.29897602848537.942169266 1157604.9854334848543.224998116
#Sta/Elev= 26
9899.119476.24729909.955474.57459927.282471.50789950.303468.43459954.455467.9118
9956.897467.70969966.761466.47819978.213464.81229986.641463.84229993.338463.2672
    9999462.964710003.41462.865410006.77462.912310010.13 463.14610023.47464.6559
10030.07465.248310036.66465.697110049.82466.400510056.39466.897810069.53468.2114
10076.15469.107710079.49470.072210082.83471.210710092.85474.835110096.19 475.939
10100.93477.3246
#Mann= 3 , 0 , 0
9899.119    0.12       09899.119    0.12       010100.93    0.12       0
#XS Ineff= 2 , 0
       0                               0
Bank Sta=9899.119,10100.93
Exp/Cntr=0.3,0.1

Type RM Length L Ch R = 1 ,2989.566,24.852200,24.852200,24.852200
XS GIS Cut Line= 6
 1157412.9431936848562.2533330431157439.56807018848571.411103874
1157462.10840229848574.2974041981157552.20211106848559.632803287
1157583.41971371848560.4887728051157611.13361988848565.611290036
#Sta/Elev= 30
9899.129468.10069903.004467.69359906.473467.18089927.285463.23339933.905462.4575
9950.009461.36599966.881460.85619970.169460.67319986.897459.39329996.984  458.93
10000.36458.976110003.74459.290710007.11459.885110010.48460.592510017.23462.1782
10020.56462.685510027.18463.1008 10033.8463.370510040.42 463.50710046.99463.4832
10050.27463.563710053.55463.939310060.12 464.94410072.74467.354710076.59467.9496
10080.31468.4212 10086.6468.912510089.94469.383410096.61470.755410100.92471.9581
#Mann= 3 , 0 , 0
9899.129    0.12       09899.129    0.12       010100.92    0.12       0
#XS Ineff= 2 , 0
       0                               0
Bank Sta=9899.129,10100.92
Exp/Cntr=0.3,0.1

Type RM Length L Ch R = 1 ,2964.714,24.852200,24.852200,24.852200
XS GIS Cut Line= 6
1157419.16428186848579.0517513191157445.15541389848589.905226753
1157471.84464117848594.9424418551157557.89081555848587.083119327
1157588.32467976848589.9405424871157616.84086324848596.630229458
#Sta/Elev= 28
9899.135463.88999903.475463.18969914.141461.11029927.301459.05879931.636458.5954
9954.462456.67969964.842455.96359978.218454.88769987.932454.62159994.578454.5291
9997.902454.5996    9999 454.70210001.24454.935210004.57455.5419 10007.9456.3716
10017.87459.083710021.15459.870810024.44460.329210041.07460.508110050.75460.2372
10060.63459.854210063.93460.025610067.22460.592810070.52461.440310073.86 462.488
 10080.6464.854310090.71468.746510100.93 472.996
#Mann= 3 , 0 , 0
9899.135    0.12       09899.135    0.12       010100.93    0.12       0
#XS Ineff= 2 , 0
       0                               0
Bank Sta=9899.135,10100.93
Exp/Cntr=0.3,0.1

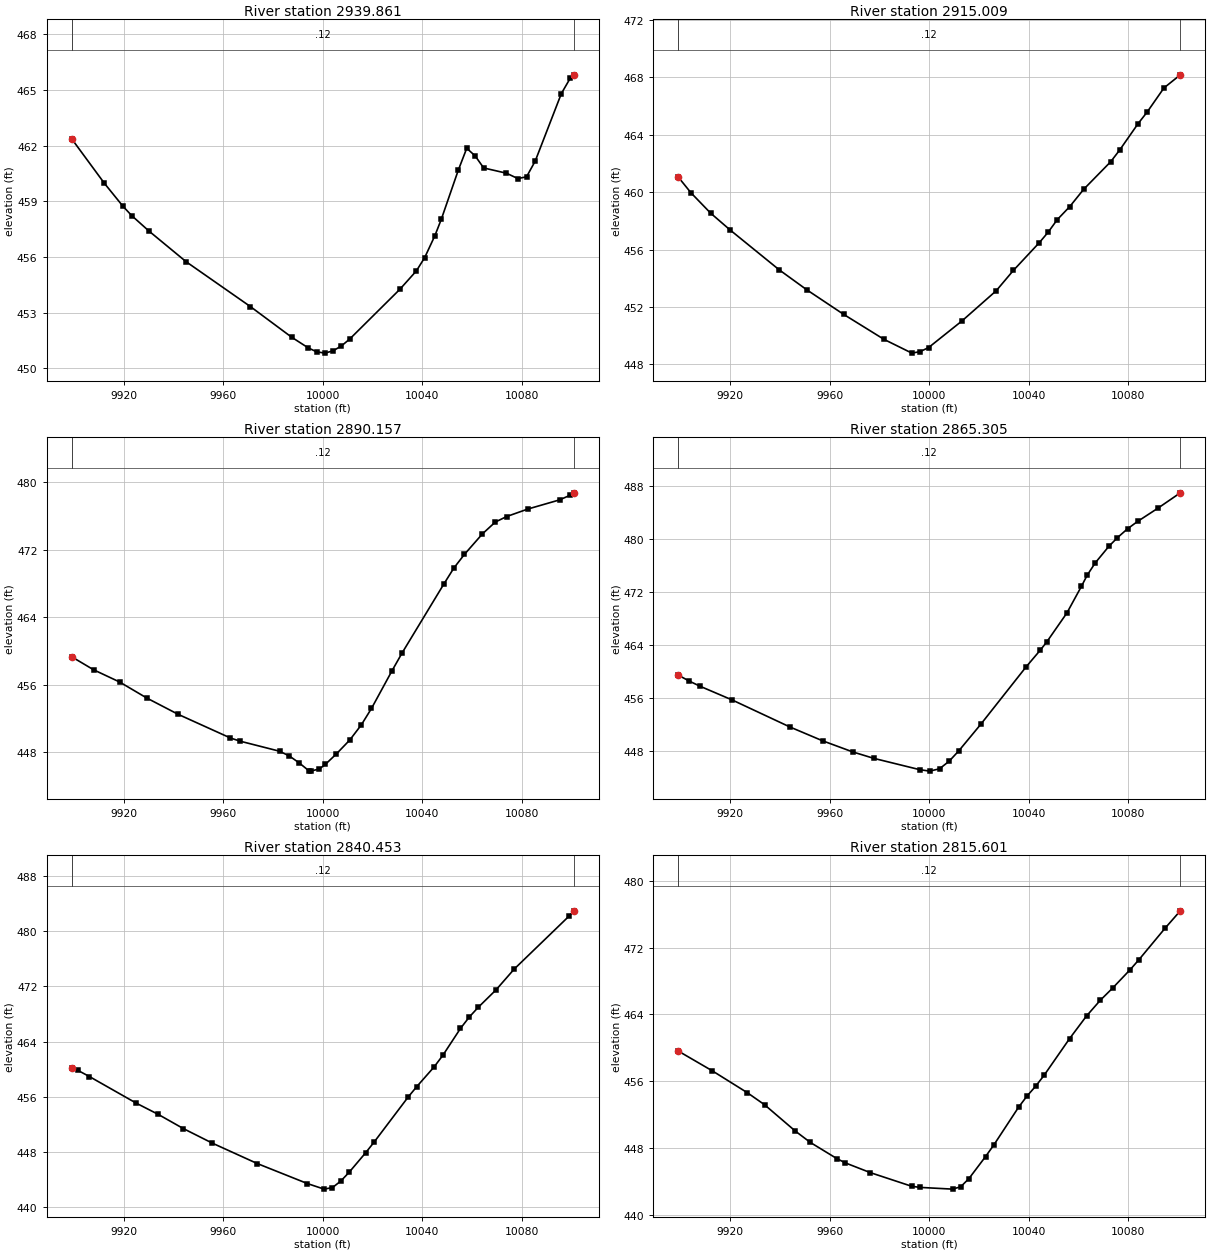
Type RM Length L Ch R = 1 ,2939.861,24.852100,24.852100,24.852100
XS GIS Cut Line= 6
1157421.42608382848587.3927354441157439.97789615848597.269754161
1157463.38728859 848606.064154871157563.75414195848624.608918424
1157589.48937344848631.7189969091157614.88128407848641.155622269
#Sta/Elev= 30
9899.088 462.3589912.213459.96539919.647458.73429923.178458.22789930.187457.3876
9945.112455.73799970.881453.32759987.524451.67179994.216451.0952 9997.51 450.889
10000.86450.815510004.21450.943110007.55451.2058 10010.9 451.58110030.97454.2483
10037.65455.2455   10041455.963310045.09457.1409 10047.7458.034410054.51460.6743
10057.91 461.85510061.31461.442110064.72460.794810073.89460.511510078.46460.2227
10081.96460.316810085.46461.168910095.96464.804610099.46465.615310100.98465.8131
#Mann= 3 , 0 , 0
9899.088    0.12       09899.088    0.12       010100.98    0.12       0
#XS Ineff= 2 , 0
       0                               0
Bank Sta=9899.088,10100.98
Exp/Cntr=0.3,0.1

Type RM Length L Ch R = 1 ,2915.009,24.852200,24.852200,24.852200
XS GIS Cut Line= 6
1157422.16054132848595.7269847541157456.02088985848618.230354139
1157478.90374197848630.1936404841157548.94829363848650.016783634
1157578.14952847848662.2485576581157605.60698163848676.433298537
#Sta/Elev= 25
9899.045461.05179904.195459.94859912.074458.53659919.953457.35789939.702454.5801
9950.759453.19349965.523451.48819981.818449.73989993.018448.78219996.383448.8899
9999.744449.1715 10013.2451.031110026.92453.127210033.81454.540610044.32456.4899
10047.88457.222910051.44458.075210056.51458.994310062.11460.198110072.95462.1148
10076.57462.930110083.96 464.76710087.65465.585410094.39467.260810100.97468.1743
#Mann= 3 , 0 , 0
9899.045    0.12       09899.045    0.12       010100.97    0.12       0
#XS Ineff= 2 , 0
       0                               0
Bank Sta=9899.045,10100.97
Exp/Cntr=0.3,0.1

Type RM Length L Ch R = 1 ,2890.157,24.852200,24.852200,24.852200
XS GIS Cut Line= 6
1157425.89210336848602.3014862221157475.09157653848641.899234972
1157503.52087547 848661.033600311157506.79186943 848664.18098927
  1157542.582092848691.3252702391157585.10492644848726.294517395
#Sta/Elev= 30
9899.024459.3061 9907.79457.77379918.255 456.325 9929.22 454.4199941.855452.4862
9962.867449.68389966.822449.30329982.641448.11479986.596447.54349990.551446.7226
9994.505445.77739995.118445.75989998.632446.0177   10001446.551610005.42447.7889
10010.85 449.44910015.46451.229710019.58453.191810027.81457.643910031.93459.7875
10048.71467.949210052.73469.838610056.98471.455610064.21473.883110069.37 475.279
10073.97475.936710082.46476.8226 10095.2477.905210099.45478.454610100.97478.7441
#Mann= 3 , 0 , 0
9899.024    0.12       09899.024    0.12       010100.97    0.12       0
#XS Ineff= 2 , 0
       0                               0
Bank Sta=9899.024,10100.97
Exp/Cntr=0.3,0.1

Type RM Length L Ch R = 1 ,2865.305,24.852200,24.852200,24.852200
XS GIS Cut Line= 6
1157423.17546055848602.9986059011157448.89117835848626.326665796
1157467.56199413848647.7324140411157486.81373694848679.097614682
1157507.97139352848712.0458039821157545.09386792 848762.69760525
#Sta/Elev= 27
9899.073 459.4179903.494 458.5159907.924457.71939920.865455.63939944.034451.5609
9957.095449.48319969.234447.79789977.682446.82599996.181445.111510000.17444.8897
10004.14445.239310008.02446.3917 10011.9447.960310020.67451.945310039.02460.6893
10044.57463.149710047.23464.413610055.37468.817710061.22472.8508 10063.5474.5107
10066.78476.401610072.33478.9351 10075.7480.212710079.77481.559810083.84482.6763
10091.97484.671110100.98486.9958
#Mann= 3 , 0 , 0
9899.073    0.12       09899.073    0.12       010100.98    0.12       0
#XS Ineff= 2 , 0
       0                               0
Bank Sta=9899.073,10100.98
Exp/Cntr=0.3,0.1

Type RM Length L Ch R = 1 ,2840.453,24.852200,24.852200,24.852200
XS GIS Cut Line= 6
1157414.96120207848600.5301047231157439.10530255848625.456895998
1157454.26644471848649.4077168791157459.47674983848664.561901281
1157472.98828729  848724.15285821157498.48412853848780.175916798
#Sta/Elev= 26
9899.136460.20969901.502459.84389906.218458.9313 9925.08455.06639933.839453.4525
9944.002451.38079955.651449.26969973.693 446.313 9993.89443.404310000.58442.6017
10003.93442.827610007.27443.765810010.62445.038210017.31447.889810020.71449.4391
10034.37455.959810037.78457.4514 10044.8460.327710048.33462.0189 10055.4465.9106
10058.94467.559910062.48468.951610069.66471.488210076.99474.514610098.99 482.178
10100.97 482.964
#Mann= 3 , 0 , 0
9899.136    0.12       09899.136    0.12       010100.97    0.12       0
#XS Ineff= 2 , 0
       0                               0
Bank Sta=9899.136,10100.97
Exp/Cntr=0.3,0.1

Type RM Length L Ch R = 1 ,2815.601,24.852200,24.852200,24.852200
XS GIS Cut Line= 6
1157399.27933119848597.0358345461157420.91741588848624.146550577
 1157431.9725817848646.2254941081157437.22129165848667.162721928
1157443.57567672848723.3677645221157464.23831376848784.106307646
#Sta/Elev= 28
9899.143 459.6329912.912457.25069926.921454.6487 9933.83453.21299946.187450.0663
9952.238448.70499962.876446.77619966.258446.26489976.405 445.089 9992.96443.4658
9996.251443.3308 10009.4 443.12210012.69443.4051   10016444.383710022.67447.0128
   10026448.4021   10036452.936710039.39454.268410042.81455.423410046.22456.7337
10056.47461.1249 10063.3463.835910068.81465.705110073.76467.160110080.79469.3542
10084.31470.542810094.85474.320410100.96 476.392
#Mann= 3 , 0 , 0
9899.143    0.12       09899.143    0.12       010100.96    0.12       0
#XS Ineff= 2 , 0
       0                               0
Bank Sta=9899.143,10100.96
Exp/Cntr=0.3,0.1

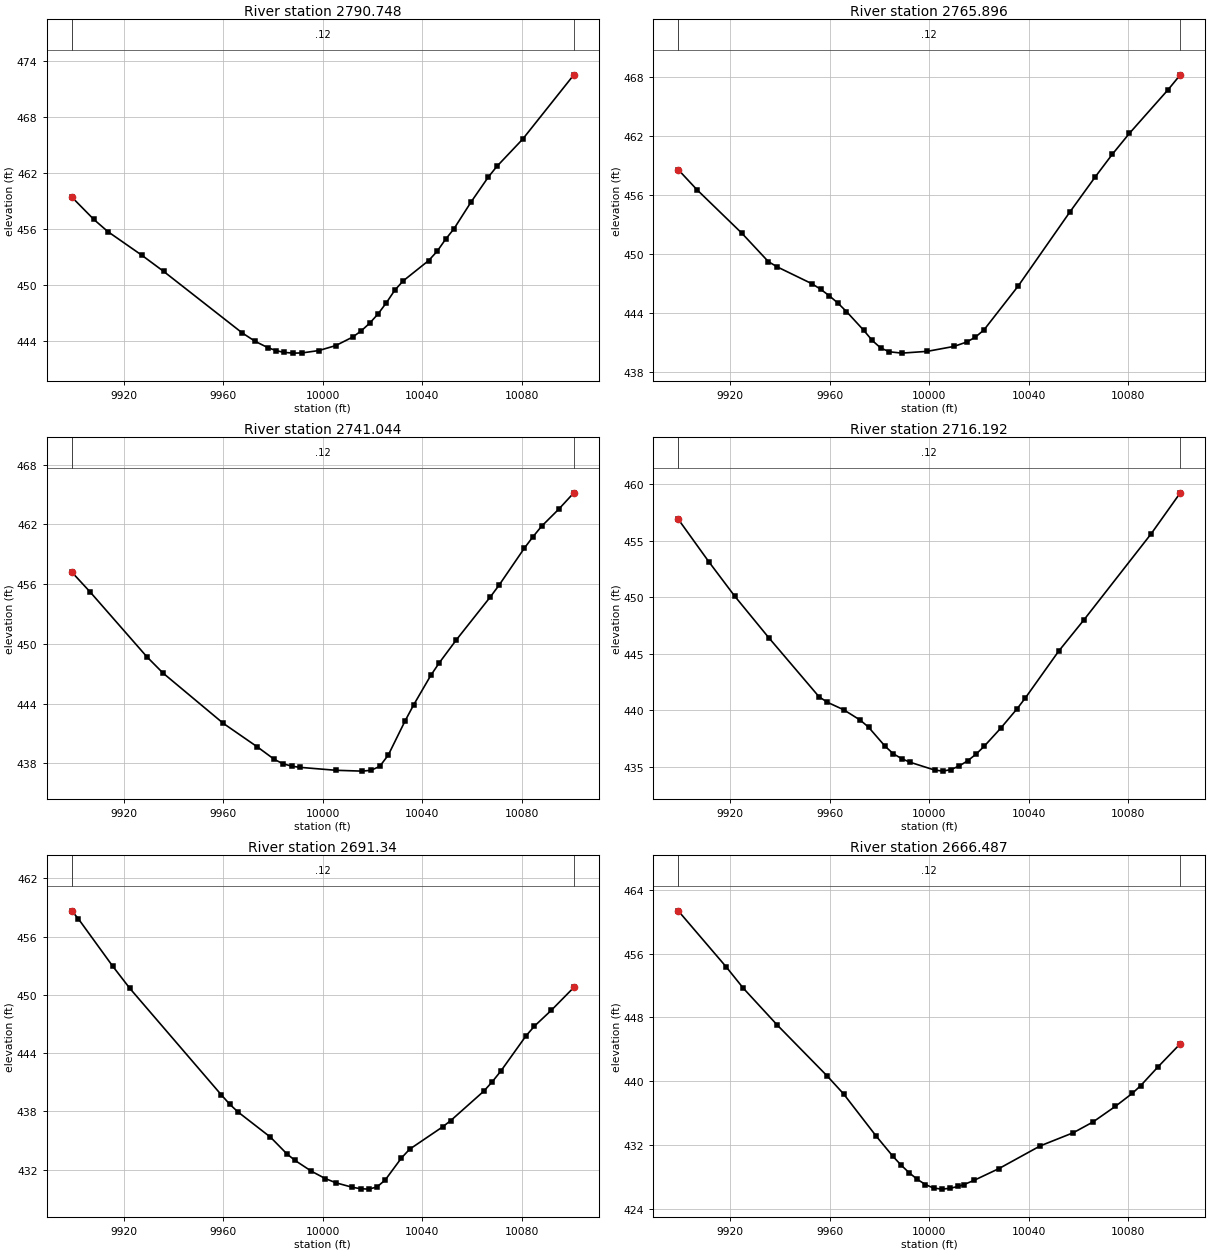
Type RM Length L Ch R = 1 ,2790.748,24.852200,24.852200,24.852200
XS GIS Cut Line= 6
1157375.87825184848598.6947333351157390.62117611848622.717006756
1157401.53379487848647.6267855891157414.16416425848690.366902194
1157429.22191248848746.6837271881157443.31778286848788.037319118
#Sta/Elev= 30
9899.052 459.4549907.922457.05449913.582455.74629927.237453.21439936.022451.4792
9967.638444.8808 9972.89443.97389977.901443.31059981.323442.98149984.467442.7996
9988.165442.72069991.586442.73969998.428442.997910005.23443.530810012.02444.4396
10015.42445.092910018.81445.913910022.21446.9119 10025.6448.1254   10029449.4796
 10032.4450.476110042.58452.641210045.98453.631510049.37454.914410052.77456.0496
10059.61458.906810066.54461.579910070.01462.734910080.41465.661410100.99472.5576
#Mann= 3 , 0 , 0
9899.052    0.12       09899.052    0.12       010100.99    0.12       0
#XS Ineff= 2 , 0
       0                               0
Bank Sta=9899.052,10100.99
Exp/Cntr=0.3,0.1

Type RM Length L Ch R = 1 ,2765.896,24.852200,24.852200,24.852200
XS GIS Cut Line= 6
1157354.25114637848604.3527863341157363.59746473848623.180146158
1157374.56562458848651.027223809 1157390.3033966848697.469997303
1157390.93585219848699.3673638811157421.38078647848794.610277568
#Sta/Elev= 27
9899.014458.54679906.523456.51139924.658452.06419935.236449.19389938.763448.6572
9952.816446.9312 9956.28446.37659959.744445.71649963.208444.97279966.672444.1084
9973.601442.20379977.065441.16119980.529440.37879983.993440.00719988.955439.8714
9999.181440.052910009.89440.551710015.09441.002510018.53441.497510021.97 442.223
10035.75446.694310056.42454.185810066.75457.804810073.64460.112610080.53462.2463
10096.09466.688810100.99468.1982
#Mann= 3 , 0 , 0
9899.014    0.12       09899.014    0.12       010100.99    0.12       0
#XS Ineff= 2 , 0
       0                               0
Bank Sta=9899.014,10100.99
Exp/Cntr=0.3,0.1

Type RM Length L Ch R = 1 ,2741.044,24.852200,24.852200,24.852200
XS GIS Cut Line= 6
1157335.24158334848612.3700793121157345.27736863848638.717111833
1157361.34618785848692.5322873281157368.10543632 848708.79928629
1157375.72461412848728.1356709021157398.51443044 848803.98129944
#Sta/Elev= 27
9899.026457.21249906.402455.21669929.191448.72049935.721447.07729960.007442.0216
9973.702439.6601 9980.55438.40379983.995437.9742 9987.54 437.7299990.688437.6151
10005.28437.316210015.86437.232910019.39437.316610022.88437.707410026.31438.8337
10033.16442.302810036.59443.902310043.44446.841110046.86448.108710053.71450.4065
10067.42454.727610070.84455.874410081.12459.626510084.55460.759110087.97461.7999
10094.82463.500610100.98465.1646
#Mann= 3 , 0 , 0
9899.026    0.12       09899.026    0.12       010100.98    0.12       0
#XS Ineff= 2 , 0
       0                               0
Bank Sta=9899.026,10100.98
Exp/Cntr=0.3,0.1

Type RM Length L Ch R = 1 ,2716.192,24.852200,24.852200,24.852200
XS GIS Cut Line= 6
1157322.04759878848615.6469154861157335.34416711848659.692685605
1157343.77543846848712.9462874581157344.00912101 848714.93258866
1157350.53995984 848759.020053631157364.13386911848812.716208902
#Sta/Elev= 27
9899.074456.90259911.437453.12179921.718450.11819935.427446.43849955.654441.2139
9958.975440.72359965.619440.05259972.262 439.1389975.584438.51779982.227436.8342
9985.549436.16469988.871435.73789992.192435.421210002.14434.726210005.46434.6295
10008.78434.767410012.09435.092210015.41435.536510018.73436.112610022.04436.8127
10028.68438.408910035.31440.138210038.63441.092410052.02445.228810062.18447.9944
10089.25455.616510100.96459.2338
#Mann= 3 , 0 , 0
9899.074    0.12       09899.074    0.12       010100.96    0.12       0
#XS Ineff= 2 , 0
       0                               0
Bank Sta=9899.074,10100.96
Exp/Cntr=0.3,0.1

Type RM Length L Ch R = 1 , 2691.34,24.852200,24.852200,24.852200
XS GIS Cut Line= 6
 1157305.6267858848615.0915712131157319.47096654848668.626194631
1157321.00743109848694.2298231951157318.03955308848751.770207382
1157322.33282447 848779.852874481157331.21377679848813.416980154
#Sta/Elev= 29
9899.068 458.6449901.745457.81259915.526452.94799922.416 450.6649959.255439.6891
9962.541438.75139965.828437.96019978.975435.34959985.559433.63449988.852432.9559
9995.438431.8465   10001431.091910005.34430.650810011.93430.190710015.23 430.046
10018.51430.0042 10021.8430.228410025.08430.937410031.64433.213610034.92434.1123
10048.16436.406210051.48437.066110064.76440.089410068.12441.044810071.51442.1241
10081.69445.768810085.09446.774110091.88448.405910100.95450.7623
#Mann= 3 , 0 , 0
9899.068    0.12       09899.068    0.12       010100.95    0.12       0
#XS Ineff= 2 , 0
       0                               0
Bank Sta=9899.068,10100.95
Exp/Cntr=0.3,0.1

Type RM Length L Ch R = 1 ,2666.487,24.852200,24.852200,24.852200
XS GIS Cut Line= 6
1157277.60565995848612.5509696061157293.01371152848665.676143955
1157295.51674151848691.2040610351157294.86180107848745.485460689
1157300.46632705848776.3336153541157310.14973842848810.098827949
#Sta/Elev= 27
9899.061 461.3839918.346454.34719925.294 451.6499938.825447.06689958.934440.6639
9965.527438.41719978.714  433.099985.287430.61229988.571429.50639991.855 428.531
9995.139   427.79998.423 427.03910001.72426.5955   10005 426.45910008.29426.5604
10011.58426.795710013.91427.022210018.15427.580910028.01 429.03510044.59431.8809
10057.93433.538510065.83434.8848 10074.8436.836810081.63438.472210085.04439.4546
10091.87441.763910100.95 444.704
#Mann= 3 , 0 , 0
9899.061    0.12       09899.061    0.12       010100.95    0.12       0
#XS Ineff= 2 , 0
       0                               0
Bank Sta=9899.061,10100.95
Exp/Cntr=0.3,0.1

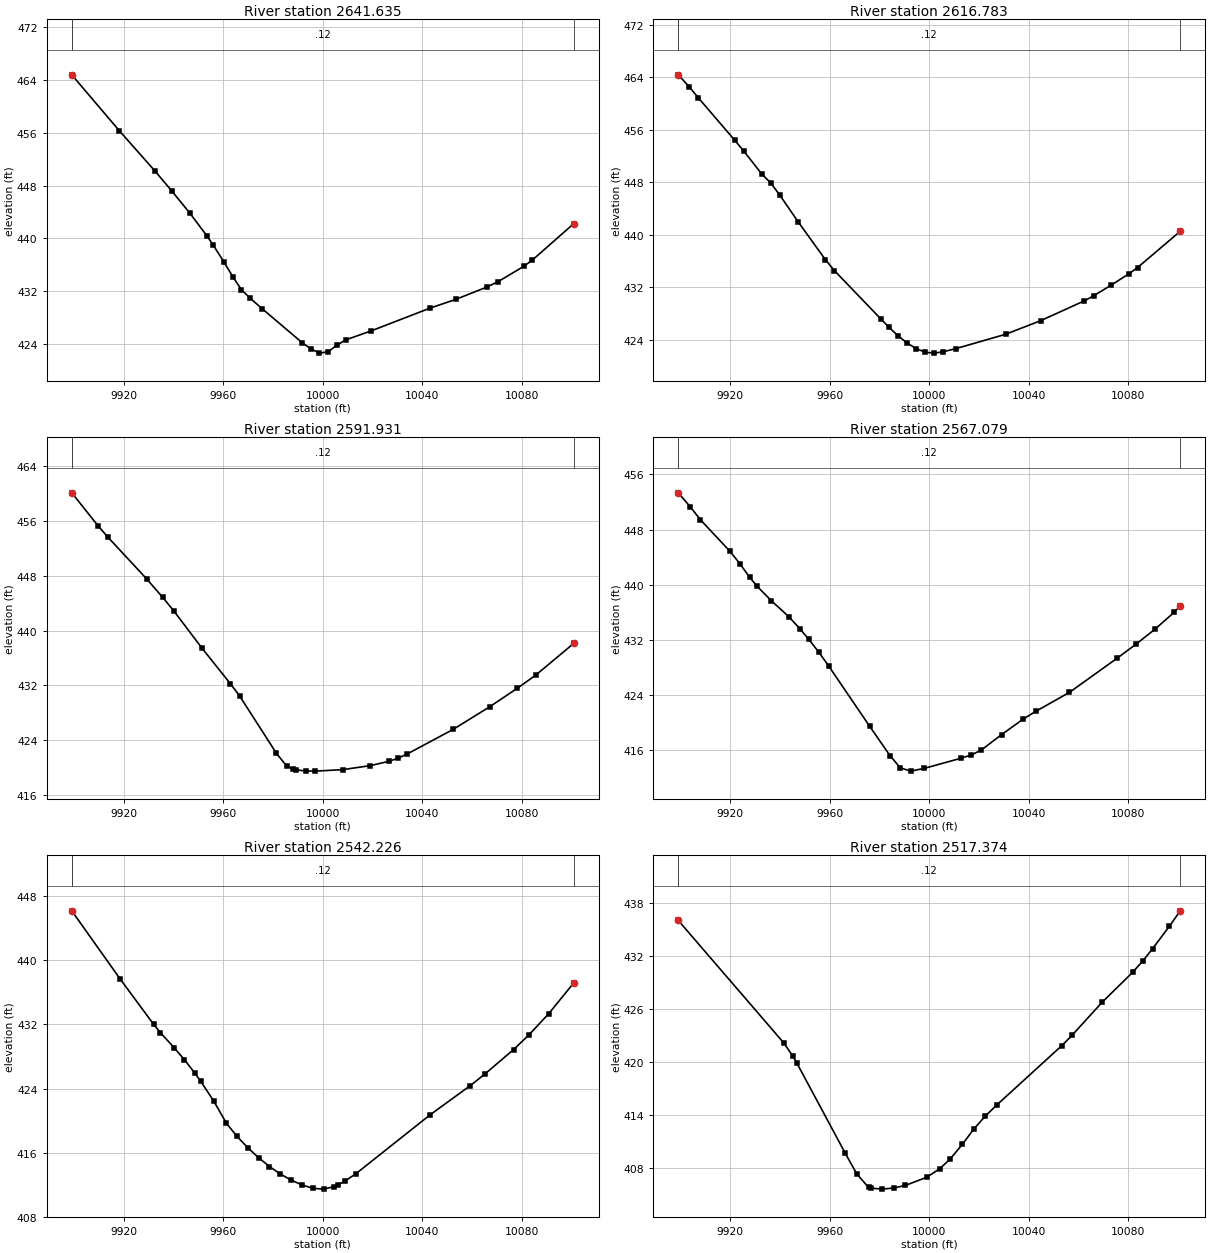
Type RM Length L Ch R = 1 ,2641.635,24.852200,24.852200,24.852200
XS GIS Cut Line= 6
1157234.90612243848619.651677817 1157248.4055955848651.772999413
1157270.27424728 848713.127936831157274.23038445848723.195312887
1157288.73255789 848777.380906561157299.57656501848810.734702861
#Sta/Elev= 26
9899.022464.78179918.192456.29039932.427450.23269939.424447.1064 9946.39443.8837
9953.356440.39819956.026438.92129960.322436.35849963.805434.18529967.288432.2176
9970.771430.9318 9975.57429.34879991.669424.20219995.152 423.2619998.635422.6076
10002.17422.816210005.69423.817710009.21424.613610019.42425.972810043.19429.4353
10053.38430.735410065.91432.610510070.43433.425710080.78 435.74410084.23436.6925
10100.98442.2435
#Mann= 3 , 0 , 0
9899.022    0.12       09899.022    0.12       010100.98    0.12       0
#XS Ineff= 2 , 0
       0                               0
Bank Sta=9899.022,10100.98
Exp/Cntr=0.3,0.1

Type RM Length L Ch R = 1 ,2616.783,24.852200,24.852200,24.852200
XS GIS Cut Line= 5
1157203.65899438 848633.327413221157247.49615694848723.200358111
1157248.39058418848724.9892124681157255.08015321848739.108246922
1157286.75552583848817.305597853
#Sta/Elev= 28
9899.006464.33439903.454462.49799907.104 460.8249921.705454.38199925.355452.7288
9932.656449.20619936.306447.82829939.957445.95379947.257441.93659958.208436.1755
9961.859434.49499980.629427.0977 9983.76425.88379987.411424.58219991.061423.4808
9994.711422.62469998.362422.071310002.02421.935110005.65422.145410010.75422.6267
 10030.7424.807210044.86426.885710062.36429.8946 10066.1430.666410073.18432.2889
10080.26434.0137 10083.8434.971710100.99440.5115
#Mann= 3 , 0 , 0
9899.006    0.12       09899.006    0.12       010100.99    0.12       0
#XS Ineff= 2 , 0
       0                               0
Bank Sta=9899.006,10100.99
Exp/Cntr=0.3,0.1

Type RM Length L Ch R = 1 ,2591.931,24.852100,24.852100,24.852100
XS GIS Cut Line= 5
1157175.12488456848647.7981578121157223.94346707 848731.85879172
1157225.26768018848734.3145972661157226.16210742848736.103451623
1157272.37301156848824.761425018
#Sta/Elev= 25
9899.002460.0832 9909.48455.31579913.448453.65069929.079447.54759935.611444.8238
9940.006 442.8859951.388437.4228 9962.77432.26149966.564430.43339981.341422.0789
9985.534420.19569987.874419.79989989.328419.66129993.122419.51489996.903 419.488
   10008419.7046 10019.1420.2883 10026.5420.9121 10030.2 421.363 10033.9421.9816
 10052.4  425.57 10067.2428.8897 10078.3431.5917 10085.7433.504310100.98438.1358
#Mann= 3 , 0 , 0
9899.002    0.12       09899.002    0.12       010100.98    0.12       0
#XS Ineff= 2 , 0
       0                               0
Bank Sta=9899.002,10100.98
Exp/Cntr=0.3,0.1

Type RM Length L Ch R = 1 ,2567.079,24.852200,24.852200,24.852200
XS GIS Cut Line= 6
1157146.16638063848666.0753645131157177.73705513848712.398094594
 1157203.9787877 848747.634090521157205.32061439848749.117162041
1157226.93837283848778.9422354041157259.42613752848833.072939501
#Sta/Elev= 30
9899.008 453.3229903.919451.26939907.889449.4343  9919.8444.8543 9923.77443.0639
9927.741441.08019930.644439.81179936.469437.68129943.622435.3232 9948.12433.5513
9951.563432.06619955.547 430.2369959.638428.16689975.981419.49849984.182415.2483
9988.273413.4749 9992.46412.98859997.952413.383710012.85414.867810016.91415.3309
10020.96416.052310029.06418.276510037.84420.546310043.01421.688110056.34424.3951
10075.47  429.3310083.12431.375410090.77433.557810098.43435.982910100.97436.9539
#Mann= 3 , 0 , 0
9899.008    0.12       09899.008    0.12       010100.97    0.12       0
#XS Ineff= 2 , 0
       0                               0
Bank Sta=9899.008,10100.97
Exp/Cntr=0.3,0.1

Type RM Length L Ch R = 1 ,2542.226,24.852200,24.852200,24.852200
XS GIS Cut Line= 6
1157122.75405106848686.5606166911157156.24824089848730.696115526
 1157185.5465683848764.2907572651157186.87529602848765.785575867
1157213.12321383848796.6531319481157246.47528743 848845.84432781
#Sta/Elev= 30
9899.019446.13659918.375437.68949931.938431.99539934.656430.96099940.176429.0896
9944.294427.60189948.413425.96289950.938424.87459956.209422.39229961.201419.6791
9965.483418.03219969.837416.6238 9974.19415.37119978.543  414.289982.896413.3497
 9987.25412.59239991.603411.99659995.956411.567710000.32411.465810004.64411.7873
10006.18412.004410008.95412.482610013.25413.374610043.25420.749510059.19424.3355
10065.03425.770310076.73428.857910082.89430.683710090.82433.313810100.95 437.175
#Mann= 3 , 0 , 0
9899.019    0.12       09899.019    0.12       010100.95    0.12       0
#XS Ineff= 2 , 0
       0                               0
Bank Sta=9899.019,10100.95
Exp/Cntr=0.3,0.1

Type RM Length L Ch R = 1 ,2517.374,24.852200,24.852200,24.852200
XS GIS Cut Line= 6
1157101.42940106848706.2784046461157136.02058747848749.541258341
1157167.31013735848781.2774784481157168.76653738848782.648207805
1157199.62267857848814.7928622461157232.22711025848859.549683098
#Sta/Elev= 26
9899.041 436.0099941.419422.16029945.177420.62589946.673419.89329966.223 409.639
9970.896407.28479975.569405.79189976.531405.69949981.139405.58899985.746405.7219
9990.353406.00639998.934406.927310004.21407.903910008.31408.9739 10013.3 410.659
10017.78412.349610022.52413.858110027.26415.1466 10053.3421.838110057.36422.9893
10069.54426.757610081.71430.116510085.77431.392710089.83432.819510096.47 435.324
10100.93 437.092
#Mann= 3 , 0 , 0
9899.041    0.12       09899.041    0.12       010100.93    0.12       0
#XS Ineff= 2 , 0
       0                               0
Bank Sta=9899.041,10100.93
Exp/Cntr=0.3,0.1