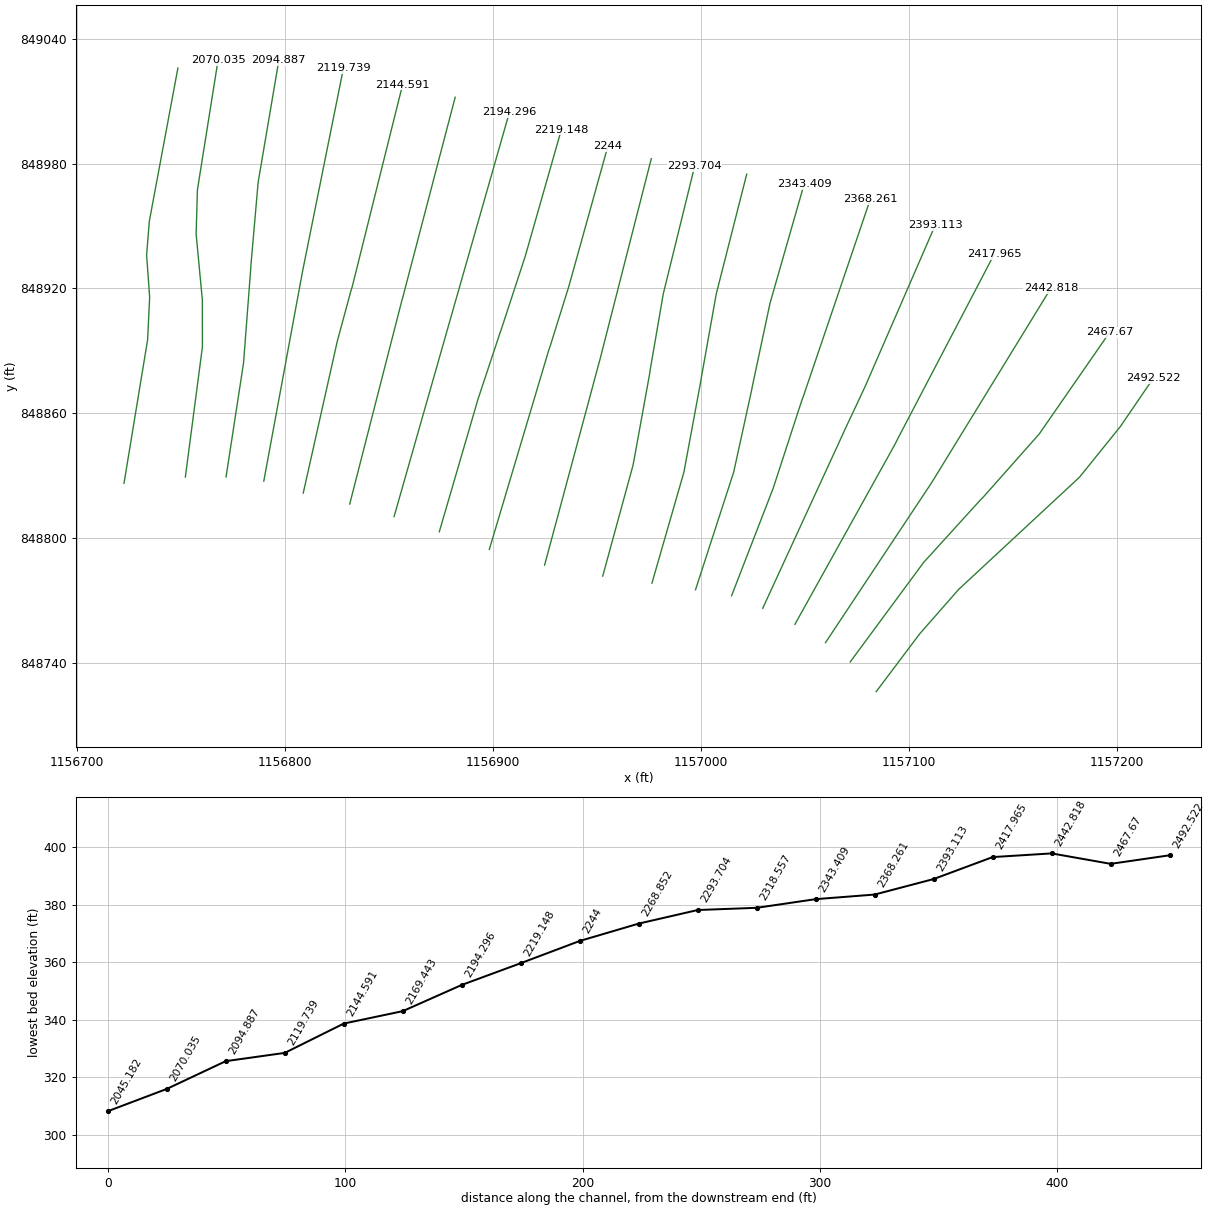
HEC-RAS study 167_ras.prj: 167

--- 167_ras.g01 (geometry) --- (continued)

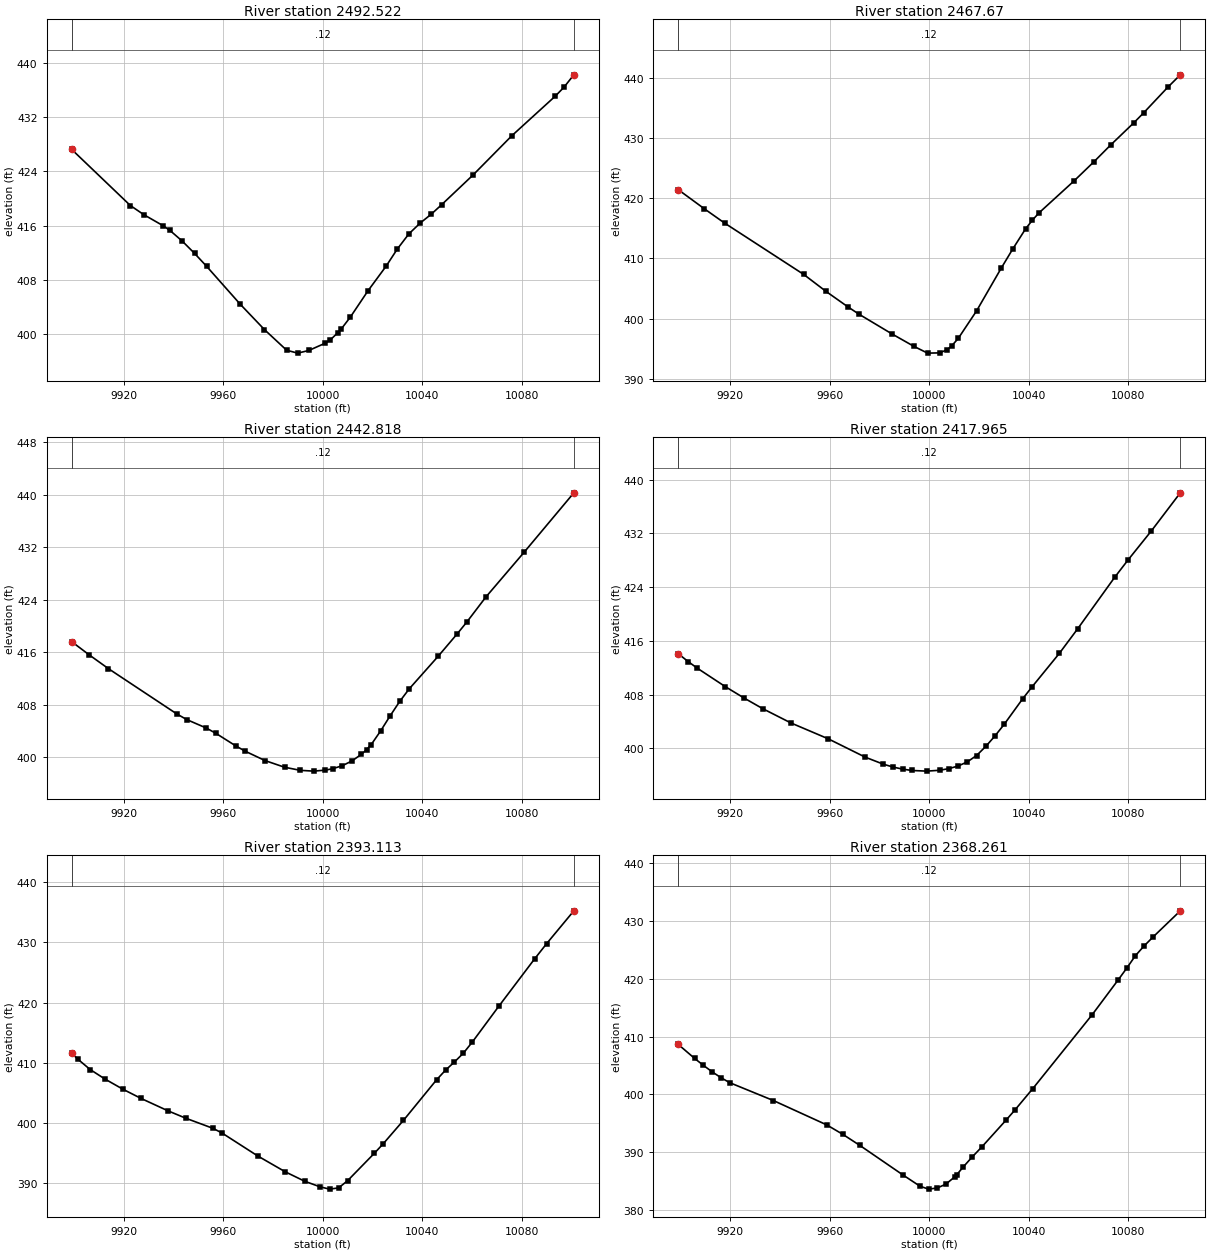
Type RM Length L Ch R = 1 ,2492.522,24.852200,24.852200,24.852200
XS GIS Cut Line= 6
1157084.20504187848726.1789136541157105.07887478 848753.92893574
1157123.82228641848775.2904520871157181.91076802848829.231758724
1157201.52911415848853.5656158111157217.43815857848876.849465396
#Sta/Elev= 30
9899.048427.21359922.606 418.9669928.063417.61019935.776415.99399938.518415.3038
9943.492413.72499948.467411.90589953.235 410.0349966.803404.43429976.533400.7015
9985.478397.65869989.922 397.2379994.365397.625610001.02398.707510003.07399.2028
10006.07400.252910007.38400.769110011.11402.554610018.18406.415110025.51410.0588
10029.93412.540510034.63414.796310039.25416.406910043.65417.696310047.86419.1061
10060.51423.4887   10076429.227310093.45435.048210096.97436.366110100.97438.2049
#Mann= 3 , 0 , 0
9899.048    0.12       09899.048    0.12       010100.97    0.12       0
#XS Ineff= 2 , 0
       0                               0
Bank Sta=9899.048,10100.97
Exp/Cntr=0.3,0.1

Type RM Length L Ch R = 1 , 2467.67,24.852200,24.852200,24.852200
XS GIS Cut Line= 6
1157071.68794446848740.4338822111157106.98944965848788.261627946
1157134.23134067848818.2446408091157135.64555427 848819.65885433
1157162.51942466848849.9623711121157196.37156199848898.817918225
#Sta/Elev= 27
9899.045421.40569909.534418.23379917.689415.85699949.494407.33199958.489404.5057
 9967.33401.92739971.763400.71839985.061397.43399993.927395.36239999.317394.2612
10004.15394.303410007.25 394.835 10009.1395.507810011.63396.698410018.99401.2608
10028.87408.335410033.56411.554710038.76414.9251 10041.5416.361510044.07417.5334
10058.22422.8631 10066.2426.035210072.88428.803110082.17432.479810086.16434.1464
10095.92438.419910100.94440.4751
#Mann= 3 , 0 , 0
9899.045    0.12       09899.045    0.12       010100.94    0.12       0
#XS Ineff= 2 , 0
       0                               0
Bank Sta=9899.045,10100.94
Exp/Cntr=0.3,0.1

Type RM Length L Ch R = 1 ,2442.818,24.852200,24.852200,24.852200
XS GIS Cut Line= 5
1157059.83401813 848749.732837891157110.68282469848826.364999672
1157114.89953625 848833.184412331157115.93514166848834.895412459
1157168.20100896848920.126009628
#Sta/Elev= 30
9899.014417.59949905.858 415.6439913.732413.50419941.294406.59199945.232405.7458
9953.106404.45439957.044403.63249964.919401.74599968.856400.90829976.731399.4985
9984.606398.48069990.982398.00619996.307397.8875   10001398.0391   10004398.2565
10007.85398.7164 10011.7399.435110015.55400.4525 10017.6401.1623 10019.4401.8945
10023.25404.0055 10027.1406.322110030.94408.509110034.79410.433410046.34415.3558
10054.04418.791110057.88 420.57410065.58424.401910080.98431.229510100.98440.2778
#Mann= 3 , 0 , 0
9899.014    0.12       09899.014    0.12       010100.98    0.12       0
#XS Ineff= 2 , 0
       0                               0
Bank Sta=9899.014,10100.98
Exp/Cntr=0.3,0.1

Type RM Length L Ch R = 1 ,2417.965,24.852200,24.852200,24.852200
XS GIS Cut Line= 5
1157045.13336345848758.5173010711157092.58406537848843.893836317
1157093.67155517848845.9459848561157094.56598241848847.734839212
1157140.88171388848936.355126735
#Sta/Elev= 30
9899.001414.08869902.982412.91839906.735411.91599917.996409.17329925.503407.4875
 9933.01405.9049 9944.27403.79349959.284401.43089974.298398.67879981.566397.6359
9985.558397.20599989.312 396.9069993.065396.7063    9999396.611110004.21396.7401
10007.91 396.98910011.61397.372810015.32397.990910019.02 398.93710022.72400.2862
10026.42401.844210030.12403.568210037.54407.361610041.23409.104110052.33414.1409
10059.74417.817910074.55425.441210080.04428.078410089.35432.368510100.99438.0323
#Mann= 3 , 0 , 0
9899.001    0.12       09899.001    0.12       010100.99    0.12       0
#XS Ineff= 2 , 0
       0                               0
Bank Sta=9899.001,10100.99
Exp/Cntr=0.3,0.1

Type RM Length L Ch R = 1 ,2393.113,24.852200,24.852200,24.852200
XS GIS Cut Line= 5
 1157029.6499703848766.2172705651157071.44307841848857.060224029
1157072.33750565848858.8490783861157078.94921037848873.004815025
 1157112.5741198 848950.38994559
#Sta/Elev= 29
9899.004411.55749901.581 410.5359906.421408.85529912.416407.26659919.638405.5747
9926.861404.05879937.695401.99969944.918400.75949955.752 399.0959959.364398.3296
9973.809 394.4969984.919391.85339992.769390.2795    9999389.348110002.74388.9796
10006.36 389.18410009.98390.384910020.79394.961510024.37396.549110032.42 400.397
10045.83407.180710049.41408.772410052.98410.124710056.56411.583110060.14413.4195
10070.87419.414610085.18427.234310090.04429.7834   10101435.2418
#Mann= 3 , 0 , 0
9899.004    0.12       09899.004    0.12       0   10101    0.12       0
#XS Ineff= 2 , 0
       0                               0
Bank Sta=9899.004,10101
Exp/Cntr=0.3,0.1

Type RM Length L Ch R = 1 ,2368.261,24.852200,24.852200,24.852200
XS GIS Cut Line= 5
1157014.67757429848772.2378967161157034.67724656848823.914389519
1157048.49123363848866.2955070731157049.20919184848868.162198266
1157081.36817352848962.836679704
#Sta/Elev= 30
9899.013408.63989905.621406.20939909.139405.01259912.657403.89349916.175402.8895
9919.693402.01989937.283398.92379958.791394.69839965.216393.07219972.118391.1409
9989.371386.04999996.273384.08829999.737383.584810003.22383.781610006.68384.4504
10010.15385.671810011.03386.064510013.61387.397710017.08 389.06610021.23390.9325
10030.94395.5558 10034.4397.257610041.63400.977310065.59413.814610075.98419.8009
10079.45421.847410082.91423.993310086.38425.670110089.84427.161610100.99431.7683
#Mann= 3 , 0 , 0
9899.013    0.12       09899.013    0.12       010100.99    0.12       0
#XS Ineff= 2 , 0
       0                               0
Bank Sta=9899.013,10100.99
Exp/Cntr=0.3,0.1

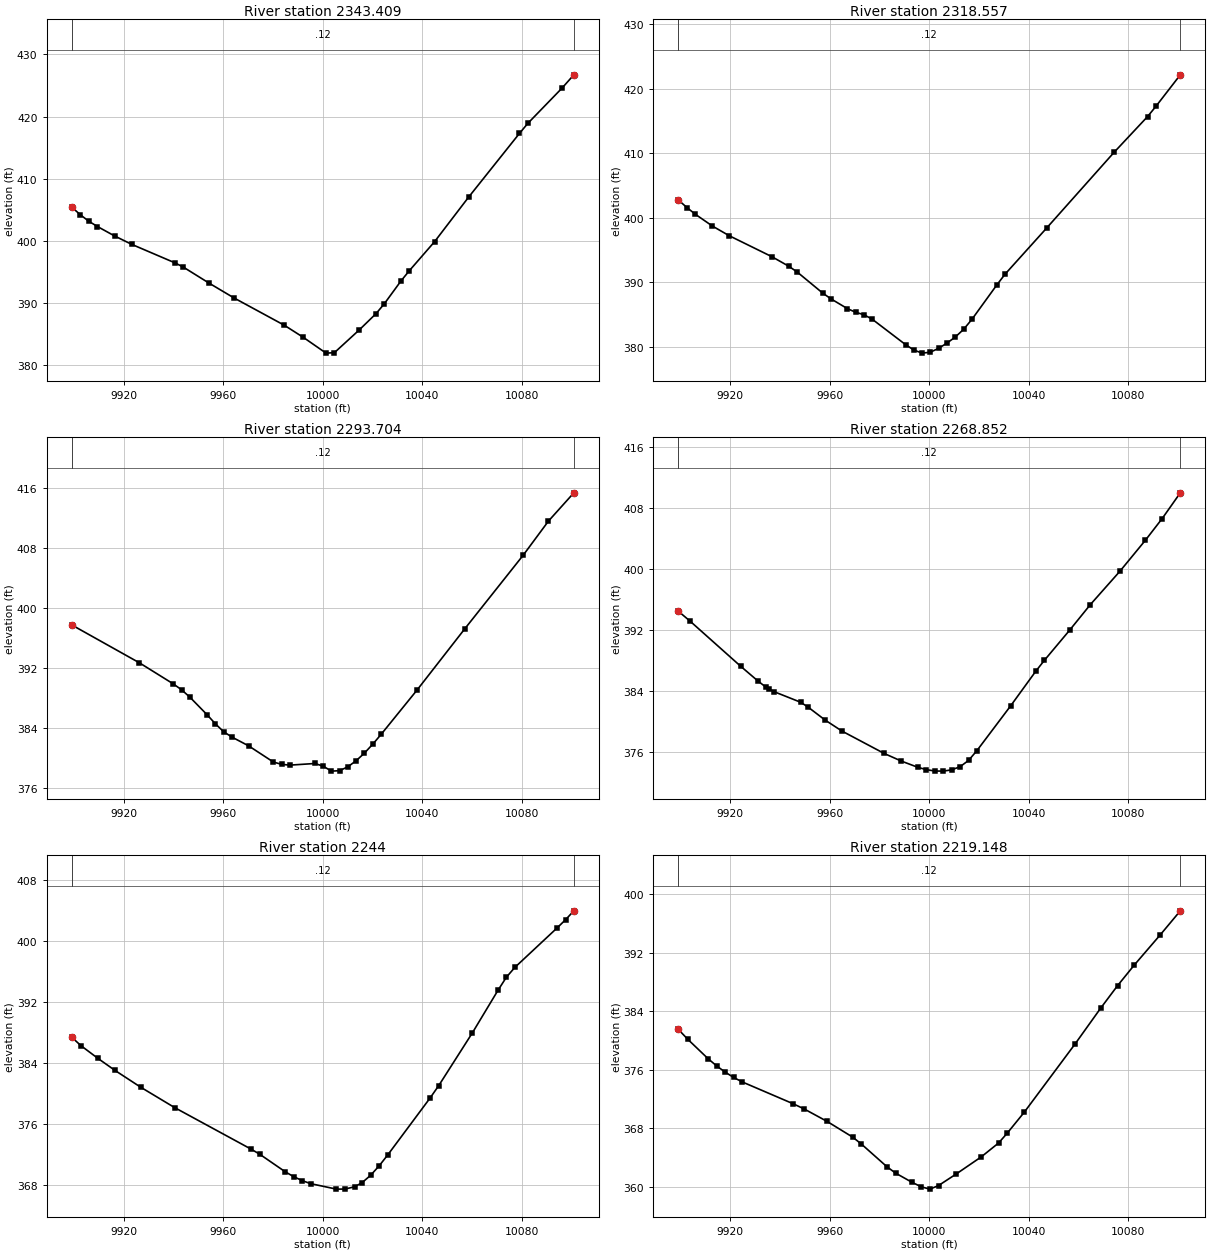
Type RM Length L Ch R = 1 ,2343.409,24.852200,24.852200,24.852200
XS GIS Cut Line= 6
1156997.36046864848775.1466975871157015.70321888848831.694550329
 1157024.3614675848871.2745900411157024.73325089848873.239730522
1157033.14535223848912.8072108951157049.54426831848970.035012049
#Sta/Elev= 25
9899.036405.44939902.457404.23229905.906403.17669909.355402.33539916.253400.8198
9923.151399.46819940.397396.51969943.846395.82719954.193 393.2529964.382390.8338
9984.532386.46359992.195384.512110001.31381.984210004.67382.057510014.73385.7387
10021.44388.339610024.79389.9394 10031.5 393.61110034.85 395.25110044.98 399.907
10058.63407.045810079.11417.307710082.52418.936210096.17424.560810100.98426.7181
#Mann= 3 , 0 , 0
9899.036    0.12       09899.036    0.12       010100.98    0.12       0
#XS Ineff= 2 , 0
       0                               0
Bank Sta=9899.036,10100.98
Exp/Cntr=0.3,0.1

Type RM Length L Ch R = 1 ,2318.557,24.852200,24.852200,24.852200
XS GIS Cut Line= 6
1156976.41753291848778.3328819791156991.75197054848831.566670231
1156999.88708398848875.3858598861157000.19583779848877.361883944
1157007.30520109848917.2543347031157021.95519392848974.881391332
#Sta/Elev= 30
9899.034402.75769902.519401.57119905.933 400.5229912.761398.7006 9919.59 397.187
9936.661393.95079943.489392.46259946.904391.55689957.085388.31159960.422387.4094
9967.096 385.8769970.433385.31419973.769384.93199977.106384.22599990.454380.2981
9993.791379.45959997.128378.976210000.46379.118710003.79379.730810007.12380.5332
10010.45 381.46710013.79382.656710017.12384.196410027.12389.528110030.45391.2128
 10047.2398.382410074.28410.113310087.82415.692810091.21417.294210100.98422.1665
#Mann= 3 , 0 , 0
9899.034    0.12       09899.034    0.12       010100.98    0.12       0
#XS Ineff= 2 , 0
       0                               0
Bank Sta=9899.034,10100.98
Exp/Cntr=0.3,0.1

Type RM Length L Ch R = 1 ,2293.704,24.852200,24.852200,24.852200
XS GIS Cut Line= 6
1156952.75234643848781.6945005031156967.36205708848835.139270454
1156975.31533502848878.9875889191156975.59047181848880.968573457
1156981.83817915848917.269219426 1156996.9037848848978.592472699
#Sta/Elev= 27
9899.031397.69389926.227 392.6489939.832389.84429943.233389.04399946.634388.0353
9953.437 385.7319956.791384.51649960.125383.45819963.459382.74589970.128381.5848
9980.131379.41889983.466379.1095  9986.8379.00829996.803 379.22510000.13378.8763
10003.45378.208210006.78 378.26710010.11378.795710013.44   379.610016.77380.6212
 10020.1381.801810023.43383.095310037.83388.9832   10057397.132610080.65407.0083
10090.78411.545310100.98415.3057
#Mann= 3 , 0 , 0
9899.031    0.12       09899.031    0.12       010100.98    0.12       0
#XS Ineff= 2 , 0
       0                               0
Bank Sta=9899.031,10100.98
Exp/Cntr=0.3,0.1

Type RM Length L Ch R = 1 ,2268.852,24.852200,24.852200,24.852200
XS GIS Cut Line= 4
 1156924.8143467848786.9698724461156950.79567736848883.524810803
1156951.33096515848885.4518466061156976.09575224848982.332047447
#Sta/Elev= 30
9899.011394.45549903.727393.15979924.112387.23519930.907385.34659934.305384.4827
9935.611384.22349937.702383.87979948.237 382.5159951.292381.86469958.087  380.18
9964.882378.7339 9981.87375.79829988.665374.8124 9995.46373.97659998.858373.6729
10002.26373.498510005.64373.482410009.03373.652110012.41374.0645 10015.8374.8833
10019.19 376.17810032.73382.034210042.89 386.59510046.28387.995310056.44391.9448
10064.81395.314610076.75399.705110086.91403.733210093.69 406.589   10101409.9672
#Mann= 3 , 0 , 0
9899.011    0.12       09899.011    0.12       0   10101    0.12       0
#XS Ineff= 2 , 0
       0                               0
Bank Sta=9899.011,10101
Exp/Cntr=0.3,0.1

Type RM Length L Ch R = 1 ,    2244,24.852100,24.852100,24.852100
XS GIS Cut Line= 5
1156898.24438686848794.5144460281156926.82821155848890.334175626
1156927.49385183848892.2201562761156936.56572769848921.283104277
 1156955.2161104848988.286937335
#Sta/Elev= 28
9899.008387.37499902.735386.26489909.582384.59179916.429383.01819926.701380.8304
9940.395378.14789971.209372.68629974.632372.02749984.903369.72169988.327369.0779
9991.751368.56129995.175368.163510005.49367.450110008.93367.456810012.91367.7698
10015.81368.301210019.24369.262410022.68370.508910026.12371.935610043.19379.4175
 10046.6381.010410060.22387.976810070.44393.516810073.84395.243510077.25396.5348
10094.28401.725710097.68402.8028   10101403.9639
#Mann= 3 , 0 , 0
9899.008    0.12       09899.008    0.12       0   10101    0.12       0
#XS Ineff= 2 , 0
       0                               0
Bank Sta=9899.008,10101
Exp/Cntr=0.3,0.1

Type RM Length L Ch R = 1 ,2219.148,24.852200,24.852200,24.852200
XS GIS Cut Line= 6
1156874.20135069848802.9805834191156892.83669174848866.821490031
 1156903.3928341848898.6054860151156904.05847439848900.491466664
1156915.53279162848935.498300185 1156932.8571499848996.231721224
#Sta/Elev= 29
9899.004381.53449902.816380.17839910.993377.52869914.411376.54969917.829375.7014
9921.247374.97499924.664374.36359945.171371.3821 9949.65370.66649958.842368.9728
9969.136366.82789972.594365.90189982.965 362.7789986.422361.91339993.047360.6549
9996.793 360.03410000.26359.721710003.72360.209610010.62361.737110020.98 364.139
10027.88366.015910031.34367.348610038.24370.227710058.71379.554110068.94384.4097
10075.77387.497310082.42 390.27910092.82394.3797   10101397.7019
#Mann= 3 , 0 , 0
9899.004    0.12       09899.004    0.12       0   10101    0.12       0
#XS Ineff= 2 , 0
       0                               0
Bank Sta=9899.004,10101
Exp/Cntr=0.3,0.1

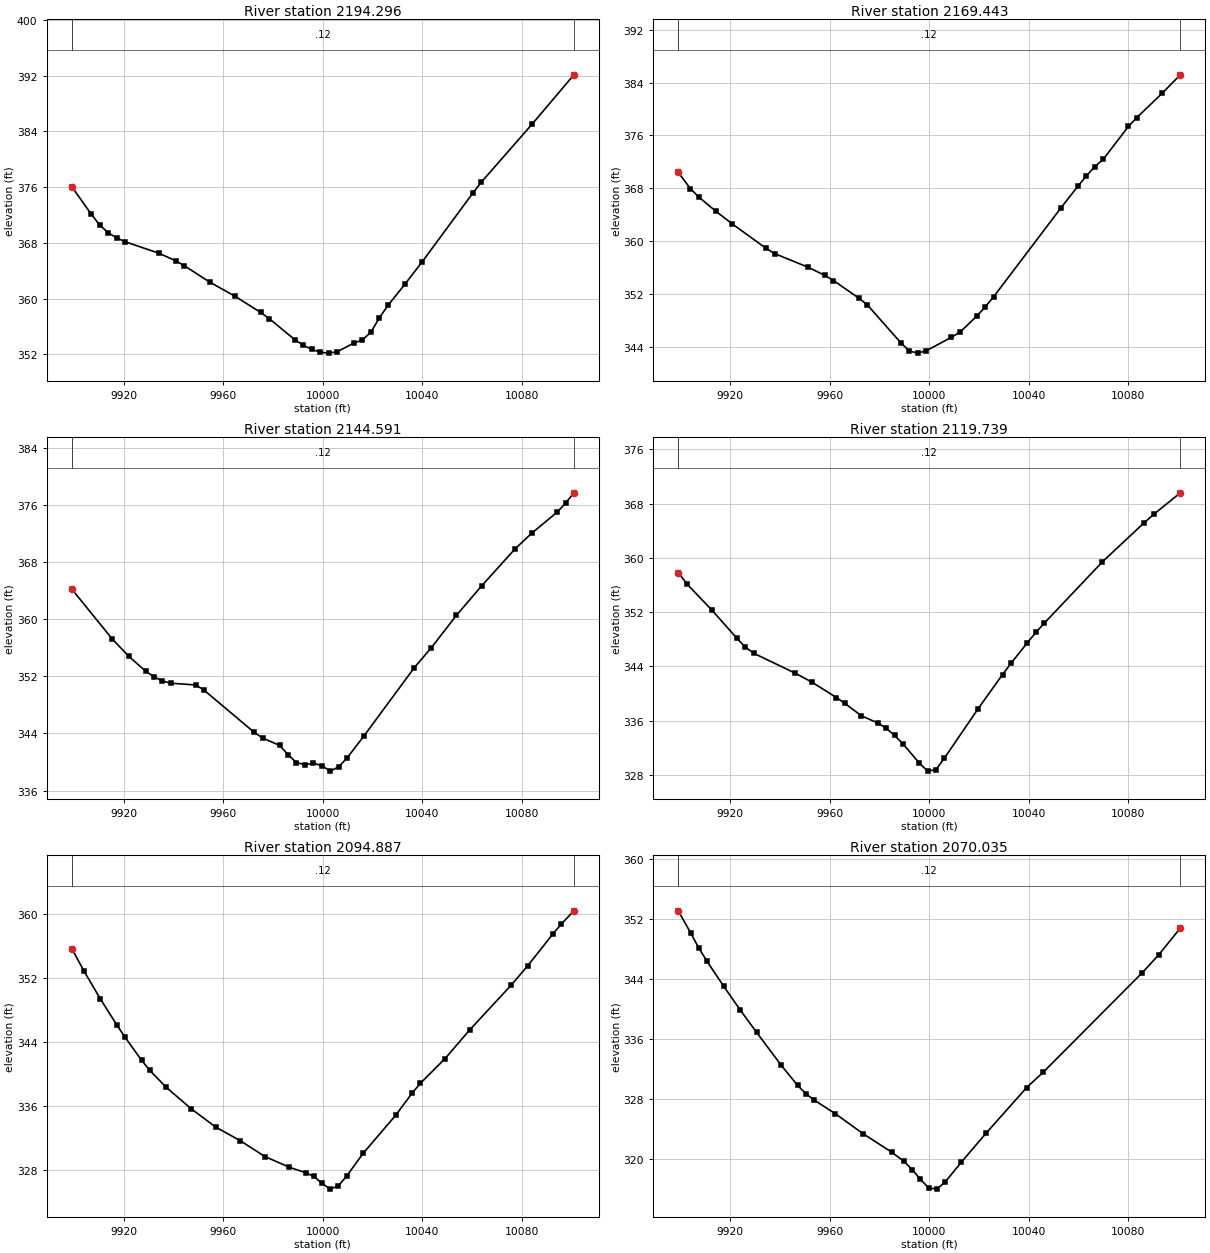
Type RM Length L Ch R = 1 ,2194.296,24.852200,24.852200,24.852200
XS GIS Cut Line= 4
1156852.47453245848810.3015314021156879.88608721848906.464949096
1156880.42757842848908.3902509611156907.88013356849004.542484371
#Sta/Elev= 30
9899.006 376.0479906.773372.14429910.184 370.5779913.596369.46099917.007368.7059
9920.419368.15139934.065366.50119940.888365.3998  9944.3364.70299954.534362.3457
9964.769360.30729975.003357.99579978.415357.11969988.649354.11619992.061353.3193
9995.472352.70549998.884352.305410002.29352.160910005.71352.346310012.53353.6218
10015.94354.039310019.35355.180410022.77357.226610026.18359.0022   10033362.0338
10039.82365.1905 10060.3375.106210063.71376.676410084.18385.018310100.99392.1024
#Mann= 3 , 0 , 0
9899.006    0.12       09899.006    0.12       010100.99    0.12       0
#XS Ineff= 2 , 0
       0                               0
Bank Sta=9899.006,10100.99
Exp/Cntr=0.3,0.1

Type RM Length L Ch R = 1 ,2169.443,24.852200,24.852200,24.852200
XS GIS Cut Line= 4
1156831.14560266848816.3228425621156855.96210055 848913.19357106
1156856.50359176848915.1188729251156881.83990637849011.855529878
#Sta/Elev= 30
9899.001370.40419903.883367.95569907.269366.67789914.043 364.5539920.816362.5887
9934.364358.9031 9937.75358.12079951.297356.04299958.071354.80139961.458 354.042
9971.618351.39119975.005350.38229988.552344.62319991.939 343.3879995.326 343.052
9998.712343.4003 10008.9345.442910012.29346.201610019.07348.643110022.46350.0243
10025.85351.559710052.99365.042710059.77368.302210063.16369.854210066.55371.2661
10069.94372.370610080.12377.354210083.51378.700510093.68382.3784   10101385.1738
#Mann= 3 , 0 , 0
9899.001    0.12       09899.001    0.12       0   10101    0.12       0
#XS Ineff= 2 , 0
       0                               0
Bank Sta=9899.001,10101
Exp/Cntr=0.3,0.1

Type RM Length L Ch R = 1 ,2144.591,24.852200,24.852200,24.852200
XS GIS Cut Line= 5
1156808.80568246848821.5850475241156825.18254043848894.606155521
1156831.75059044848918.8931207761156832.36014195848920.797969053
1156856.54686614849017.815227649
#Sta/Elev= 30
9899.006364.22699915.271357.24379921.995354.7948 9928.72352.72989932.082351.9455
9935.445 351.3679938.807351.04159948.894350.79769952.256350.0612 9972.43 344.151
9975.814343.36689982.611342.3349 9986.01341.03779989.408339.92749992.807339.6333
9996.206339.84989999.613339.491410003.02338.7298 10006.4339.335110009.78340.5879
10016.54343.648610036.83353.232310043.59355.985810053.74360.544210063.88364.6688
10077.41369.882810084.17372.090710094.31375.008610097.69376.272110100.99377.7075
#Mann= 3 , 0 , 0
9899.006    0.12       09899.006    0.12       010100.99    0.12       0
#XS Ineff= 2 , 0
       0                               0
Bank Sta=9899.006,10100.99
Exp/Cntr=0.3,0.1

Type RM Length L Ch R = 1 ,2119.739,24.852200,24.852200,24.852200
XS GIS Cut Line= 4
1156789.84579176848827.3436329031156808.01641019848925.674403623
1156808.37418112848927.6421434331156828.10637298849025.672243056
#Sta/Elev= 29
9899.004357.84119902.615356.11459912.624352.26459922.633348.1339 9925.97346.8518
9929.306 345.9419945.988343.00679952.661341.6983 9962.67339.39299966.006338.5485
9972.679336.70289979.352335.63689982.688334.85479986.025333.80979989.361332.5818
9996.034329.7154 9999.37328.539310002.71328.764810006.06330.438310019.44337.6355
10029.48342.794310032.83344.421810039.52347.514610042.87348.996910046.22350.3539
10069.64359.418810086.38365.166910090.61366.5203   10101369.6055
#Mann= 3 , 0 , 0
9899.004    0.12       09899.004    0.12       0   10101    0.12       0
#XS Ineff= 2 , 0
       0                               0
Bank Sta=9899.004,10101
Exp/Cntr=0.3,0.1

Type RM Length L Ch R = 1 ,2094.887,24.852200,24.852200,24.852200
XS GIS Cut Line= 6
1156771.71620018848829.3826061381156780.11904255848884.147337463
 1156783.5095032848928.591430754 1156783.6204433848930.588351457
1156787.13298297848970.9543473931156797.08690613849029.573250842
#Sta/Elev= 30
9899.021355.6408 9903.87352.88369910.508349.38099917.147346.12219920.466344.5926
9927.104341.72259930.423340.45959937.062 338.343 9947.02 335.6919956.955333.3944
9966.826331.70219976.697329.73149986.568328.39639993.149327.70349996.439327.2552
9999.729326.375710003.02325.670210006.31 326.10110009.61 327.30110016.19330.1194
10029.37334.892510035.95337.650310039.24338.8533 10049.2341.944710059.19 345.551
10075.83351.102810082.48 353.52410092.47357.433810095.79358.653810100.98  360.35
#Mann= 3 , 0 , 0
9899.021    0.12       09899.021    0.12       010100.98    0.12       0
#XS Ineff= 2 , 0
       0                               0
Bank Sta=9899.021,10100.98
Exp/Cntr=0.3,0.1

Type RM Length L Ch R = 1 ,2070.035,24.852200,24.852200,24.852200
XS GIS Cut Line= 6
1156752.15013441848829.2950580191156760.35115342848891.867635316
1156760.31237633848914.4957975481156757.32794998848946.170705023
 1156757.9560957848967.3670934961156767.87357744849029.708246941
#Sta/Elev= 27
9899.027353.07459903.971350.16469907.295348.12059910.619346.34719917.267343.0523
9923.915339.88879930.563336.88339940.476332.49699947.066329.81879950.361328.7219
9953.655327.88439962.172326.06719973.377323.3953  9984.8320.95099989.804 319.721
  9993.1318.61969996.397317.33349999.696316.1885   10003316.015810006.29316.9337
10012.88 319.59710022.73323.425410039.16329.545510045.81331.583410085.67344.8415
10092.32347.236410100.95 350.773
#Mann= 3 , 0 , 0
9899.027    0.12       09899.027    0.12       010100.95    0.12       0
#XS Ineff= 2 , 0
       0                               0
Bank Sta=9899.027,10100.95
Exp/Cntr=0.3,0.1

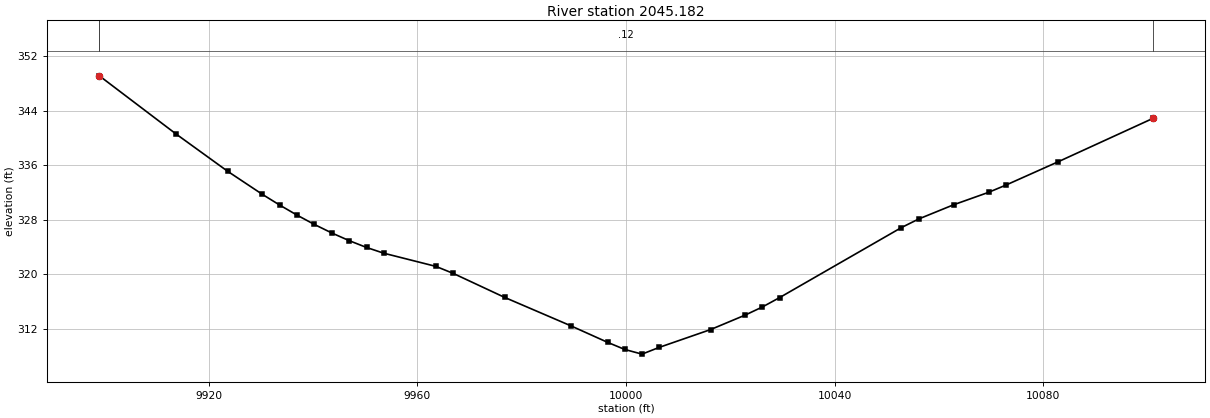
Type RM Length L Ch R = 1 ,2045.182,24.852200,24.852200,24.852200
XS GIS Cut Line= 6
1156722.65655639848826.2954701421156734.00005047848895.196125502
1156734.99293277848915.6982175081156733.53049328848936.049445241
1156734.84525685 848952.331140681156748.56876225849025.885066316
#Sta/Elev= 30
9899.048349.12759913.684340.62549923.659335.10239930.309331.71629933.634330.1427
9936.959328.66479940.284327.29639943.609326.05079946.934324.92639950.259323.9256
9953.584323.07639963.559321.14469966.884320.11449976.762 316.5839989.403312.4266
 9996.48309.98989999.774308.942210003.07308.260110006.36309.249210016.23311.8704
10022.81313.982410026.15315.186110029.44 316.559 10052.8326.846710056.14328.1161
10062.81330.195610069.49332.015410072.82333.080810082.84 336.50710100.97342.8654
#Mann= 3 , 0 , 0
9899.048    0.12       09899.048    0.12       010100.97    0.12       0
#XS Ineff= 2 , 0
       0                               0
Bank Sta=9899.048,10100.97
Exp/Cntr=0.3,0.1