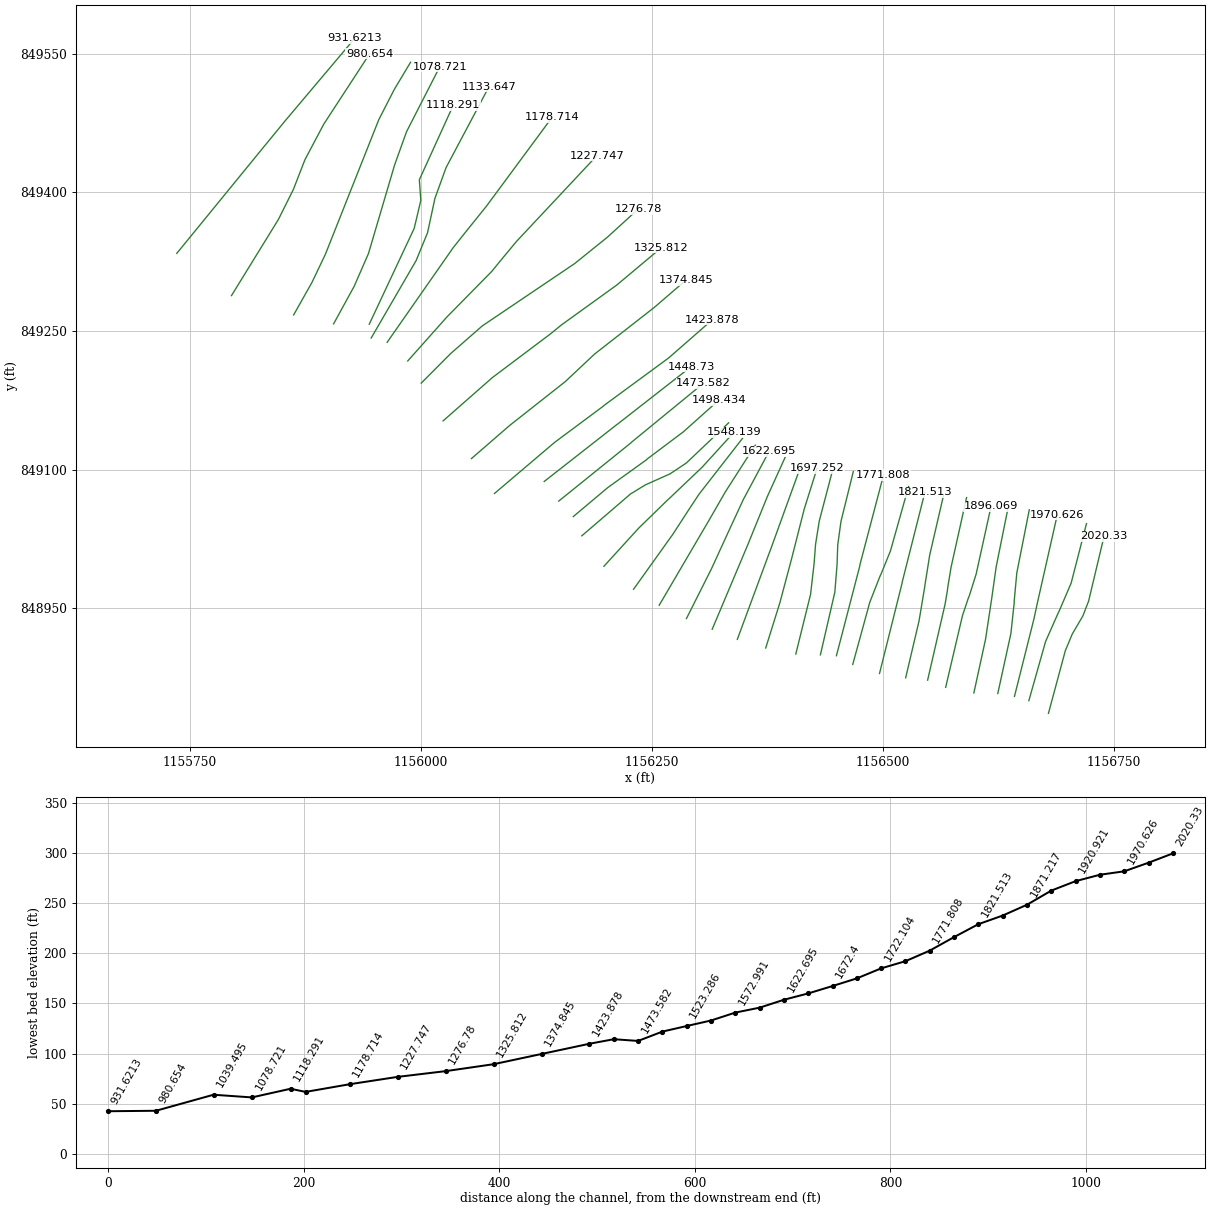
HEC-RAS study 167_ras.prj: 167

--- 167_ras.g01 (geometry) --- (continued)

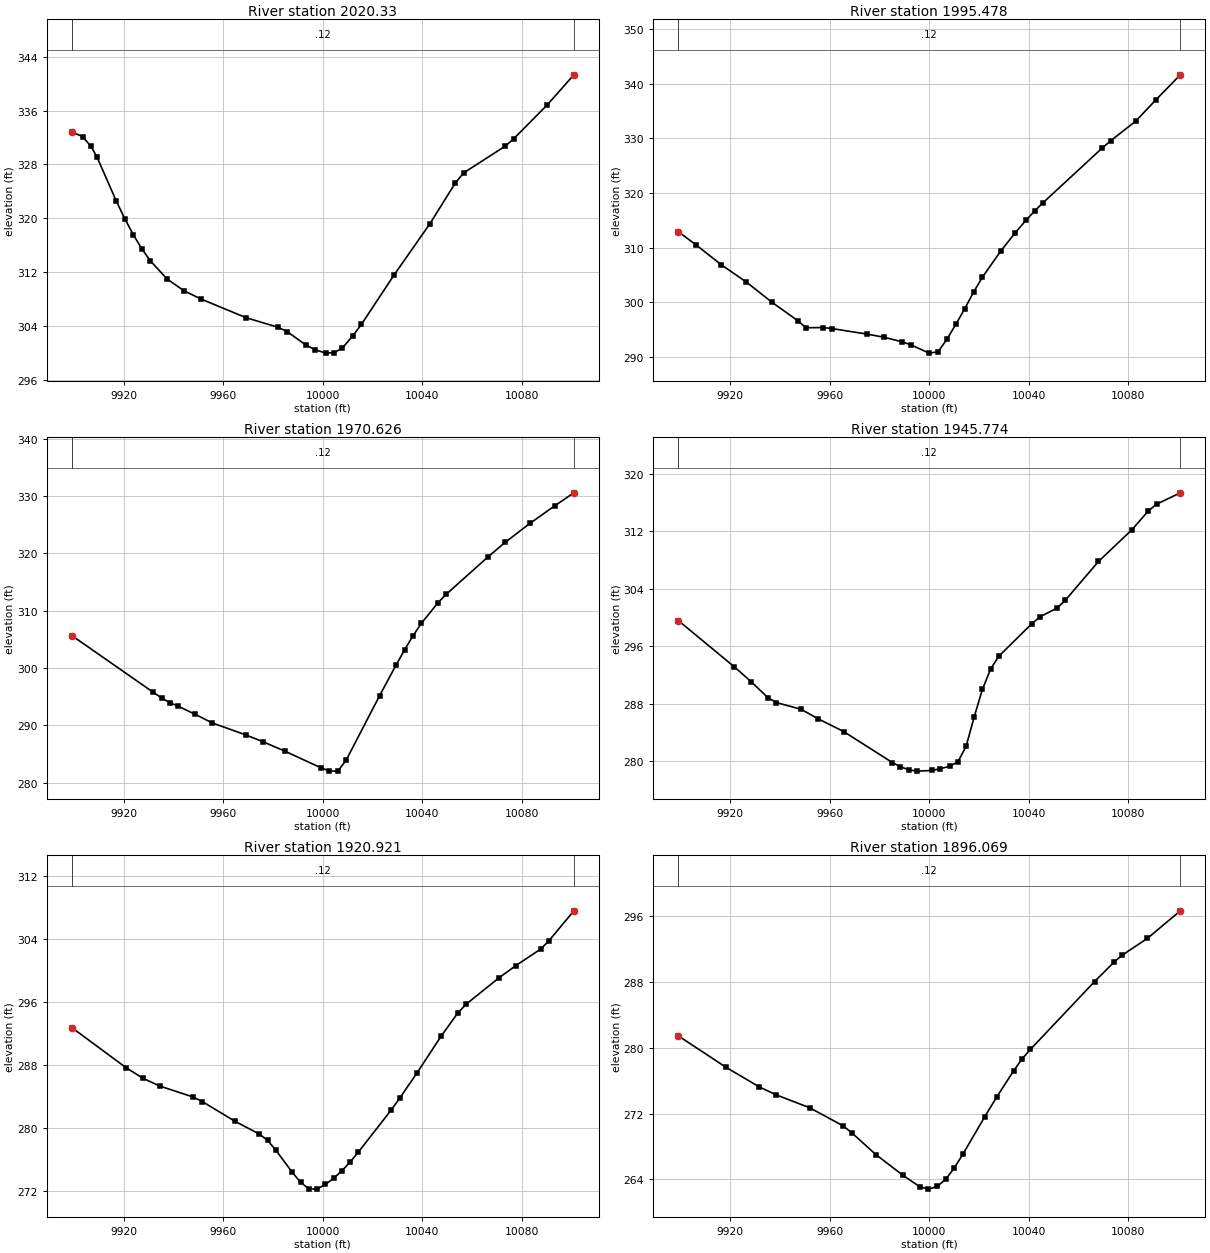
Type RM Length L Ch R = 1 , 2020.33,24.852200,24.852200,24.852200
XS GIS Cut Line= 6
1156679.04844559848836.5410908371156697.29756181848904.266118817
1156704.73414599848922.1443406371156716.38556012848942.081144454
1156722.51599154848957.9323403591156739.27635728849028.260054558
#Sta/Elev= 30
9899.051332.82329903.396332.13579906.794 330.6739909.244329.04979916.987322.5215
9920.385319.90279923.783317.55439927.181315.47429930.579313.68679937.374310.9584
 9944.17309.20479950.966 307.9849969.191305.19339982.112303.76149985.665303.1273
9993.057301.17259996.851300.450410001.13299.929910004.55300.007210007.83300.6744
10012.05302.486710015.55304.219110028.65311.544510043.09319.1868 10053.2325.1765
10056.58 326.72310073.44330.732110076.81 331.822 10090.3 336.87210100.95341.3176
#Mann= 3 , 0 , 0
9899.051    0.12       09899.051    0.12       010100.95    0.12       0
#XS Ineff= 2 , 0
       0                               0
Bank Sta=9899.051,10100.95
Exp/Cntr=0.3,0.1

Type RM Length L Ch R = 1 ,1995.478,24.852200,24.852200,24.852200
XS GIS Cut Line= 6
1156657.86330304848850.3269034921156675.96257365848914.306834783
1156689.50109896848944.8946546611156690.43687445848946.662230464
1156703.61111659848977.4073683711156720.22105296849041.783550808
#Sta/Elev= 30
9899.059312.91869906.141310.52189916.369306.85289926.366303.70889936.827 299.945
9947.056296.62699950.465295.30539957.284 295.3449960.694295.16419974.791294.1564
9981.967 293.5499989.143292.71899992.731292.15019999.938290.653810003.55290.8989
10007.12293.219710010.69295.944910014.26298.799510017.83301.860610021.39304.5893
 10028.8309.405510034.45312.6552   10039315.071710042.39316.723310045.77318.2334
10069.49328.228910072.88329.554110083.05333.1938 10091.2337.121710100.93341.6629
#Mann= 3 , 0 , 0
9899.059    0.12       09899.059    0.12       010100.93    0.12       0
#XS Ineff= 2 , 0
       0                               0
Bank Sta=9899.059,10100.93
Exp/Cntr=0.3,0.1

Type RM Length L Ch R = 1 ,1970.626,24.852200,24.852200,24.852200
XS GIS Cut Line= 5
1156642.28344745848854.8903056181156663.20398312848938.095345534
1156666.22338496848951.9744128951156666.61561729848953.935574235
  1156688.669205849051.470895888
#Sta/Elev= 26
9899.001305.68919931.769295.79259935.152294.79069938.535293.96379941.917293.3444
9948.683291.94299955.449290.45929968.981288.36169975.747287.20259984.796285.5156
9999.317282.604310002.67 282.06210006.04282.0408 10009.4283.960910022.85295.1972
10029.58 300.63410032.94303.217110036.31305.663310039.67307.8226 10046.4 311.448
10049.76312.928810066.58319.450210073.31321.9217 10083.4325.271610093.49328.3645
   10101330.5767
#Mann= 3 , 0 , 0
9899.001    0.12       09899.001    0.12       0   10101    0.12       0
#XS Ineff= 2 , 0
       0                               0
Bank Sta=9899.001,10101
Exp/Cntr=0.3,0.1

Type RM Length L Ch R = 1 ,1945.774,24.852200,24.852200,24.852200
XS GIS Cut Line= 6
1156624.22115802848858.0141070551156638.42622417848922.975146905
1156642.00871192 848956.242705781156642.00871197 848958.24270578
1156644.81308849848988.4801726851156658.32138502849056.750712841
#Sta/Elev= 30
9899.044299.57539921.659293.11059928.375291.05569935.092288.8436 9938.45288.1596
9948.526287.20989955.242285.9089 9965.54284.1275 9985.12279.8121 9988.42279.2194
 9991.72278.80029995.019278.6124   10001278.702710004.48278.9482 10008.2279.2973
10011.49279.902510014.79282.041510018.08286.170910021.38289.998610024.67292.8231
10027.97 294.60410041.29299.150210044.64  300.1110051.33301.294710054.67302.3749
10068.05307.793310081.43312.182510088.11314.827810091.46315.773810100.96317.3444
#Mann= 3 , 0 , 0
9899.044    0.12       09899.044    0.12       010100.96    0.12       0
#XS Ineff= 2 , 0
       0                               0
Bank Sta=9899.044,10100.96
Exp/Cntr=0.3,0.1

Type RM Length L Ch R = 1 ,1920.921,24.852200,24.852200,24.852200
XS GIS Cut Line= 6
1156598.34507216  848858.66604841156611.00888121 848916.82009819
1156617.04395559848956.8379002241156617.36242053848958.812382456
1156622.52210858848995.2869862391156635.01062409849057.190819376
#Sta/Elev= 30
9899.013292.77849920.956  287.669927.671286.32849934.387285.34989947.818283.9493
9951.543283.37059964.534280.88789974.488279.23579977.806278.43749981.124 277.184
 9987.76274.35559991.078273.10839994.396272.26819997.714272.238810001.03272.8374
10004.35273.610110007.66 274.56110010.98275.682610014.29276.941510027.54282.3136
10030.86283.765510037.84286.984710047.52291.652310054.21294.592810057.56295.7246
10070.95299.123110077.64300.655510087.68302.769610091.03303.840310100.99307.6245
#Mann= 3 , 0 , 0
9899.013    0.12       09899.013    0.12       010100.99    0.12       0
#XS Ineff= 2 , 0
       0                               0
Bank Sta=9899.013,10100.99
Exp/Cntr=0.3,0.1

Type RM Length L Ch R = 1 ,1896.069,24.852100,24.852100,24.852100
XS GIS Cut Line= 6
1156567.81048216848864.6918487411156585.96248262848942.062587354
1156592.43601165848961.5180386521156593.29892269848963.322307072
1156600.83554568848987.3016205851156616.93888022849060.382395747
#Sta/Elev= 25
9899.024281.45699918.228277.62739931.707275.22589938.447274.26719951.927272.6973
9965.406270.48869968.776 269.6669978.496267.01299989.269264.51439996.185263.0846
9999.676262.800210003.19263.125610006.63264.008210010.06265.3784 10013.5267.0454
10022.28271.590710027.23274.063810033.95277.206110037.31278.637210040.67279.7983
 10066.5288.063510074.27290.411910077.63291.276810087.71293.305810100.97296.6628
#Mann= 3 , 0 , 0
9899.024    0.12       09899.024    0.12       010100.97    0.12       0
#XS Ineff= 2 , 0
       0                               0
Bank Sta=9899.024,10100.97
Exp/Cntr=0.3,0.1

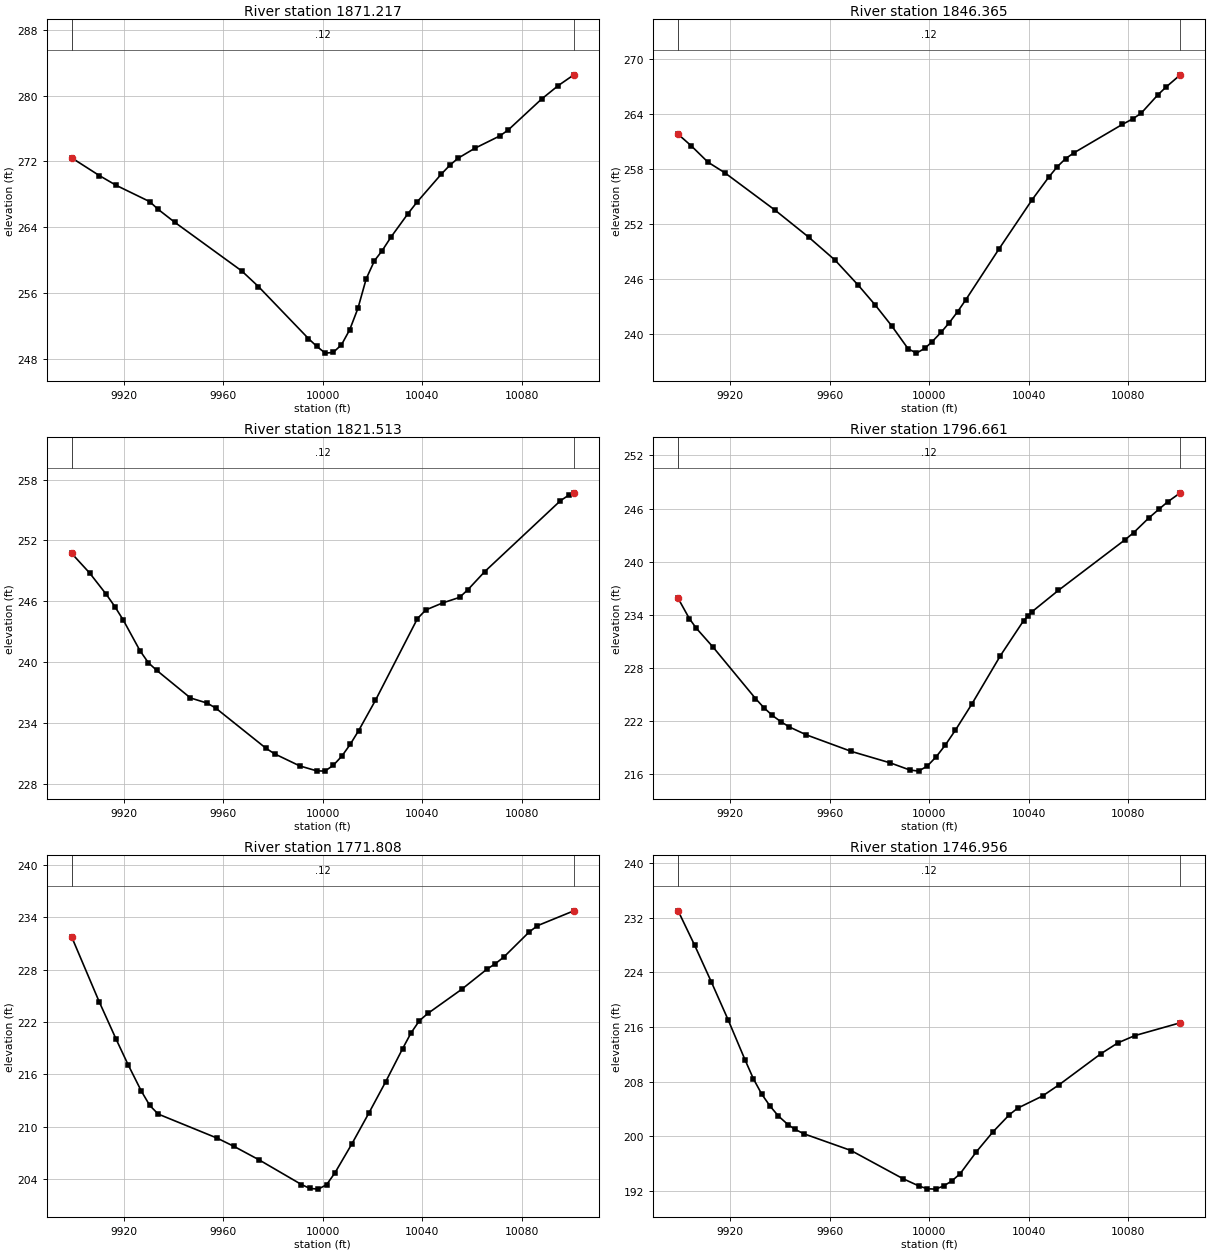
Type RM Length L Ch R = 1 ,1871.217,24.852200,24.852200,24.852200
XS GIS Cut Line= 6
1156548.30367706848872.492823678 1156567.2083601848954.720951057
1156569.79914079848970.1187459361156569.98021234848972.110532344
1156573.67071572848994.6450959981156590.44960188849069.947587996
#Sta/Elev= 30
9899.012272.42359910.191270.26239916.924269.0813 9930.39267.10259933.756266.1726
9940.489264.58599967.421258.67169974.153256.76759994.223250.4567 9997.55249.5133
   10001248.678710004.18248.760810007.51249.682610010.83251.514710014.16254.1356
10017.48257.7231 10020.8 259.92110023.83261.112410027.49262.812810034.22265.6175
10037.83267.015910047.66270.441410051.02271.497810054.38272.374110061.11273.5805
10071.19275.086710074.55275.8032   10088279.571810094.72281.212910100.98282.5196
#Mann= 3 , 0 , 0
9899.012    0.12       09899.012    0.12       010100.98    0.12       0
#XS Ineff= 2 , 0
       0                               0
Bank Sta=9899.012,10100.98
Exp/Cntr=0.3,0.1

Type RM Length L Ch R = 1 ,1846.365,24.852200,24.852200,24.852200
XS GIS Cut Line= 6
1156524.52719383848874.9857004471156538.99574943848936.459280831
1156545.06031413848972.7875038651156545.30838366848974.772059611
1156550.56322956849007.8419356931156565.57588485849072.625804687
#Sta/Elev= 30
9899.016261.75949904.277260.50249911.018258.71249917.759257.55959937.981253.4759
9951.463250.53599962.169 248.0039971.561245.24749978.214243.13729984.866240.8542
9991.519238.33339994.845237.85829998.171238.3685   10001239.057510004.81240.1375
10008.13241.199710011.45242.393310014.77243.707410028.06249.229510041.44254.6295
10048.18257.112310051.55258.223910054.91259.111110058.28259.740910077.66262.8316
10081.86263.438210085.22264.049510091.96266.062310095.33266.930110100.99268.2488
#Mann= 3 , 0 , 0
9899.016    0.12       09899.016    0.12       010100.99    0.12       0
#XS Ineff= 2 , 0
       0                               0
Bank Sta=9899.016,10100.99
Exp/Cntr=0.3,0.1

Type RM Length L Ch R = 1 ,1821.513,24.852200,24.852200,24.852200
XS GIS Cut Line= 4
1156496.22075717848879.6784362371156520.47347865848976.685519467
1156520.81616106848978.6559429671156545.31337984849075.602742338
#Sta/Elev= 30
9899.007250.71899906.212248.79179912.976246.66439916.358245.47879919.739244.1542
9926.503241.11579929.885239.92639933.288239.16999946.794236.46039953.558235.9488
9956.939 235.466 9977.23231.48749980.612230.95149990.758229.75819997.521229.2751
10000.87229.244810004.26229.824310007.64230.710410011.02231.873410014.41233.2282
10021.18236.2198 10038.1244.293410041.48245.142210048.25245.834110055.02246.3778
 10058.4247.142810065.17248.924910095.62 255.91510099.01256.471110100.99256.6893
#Mann= 3 , 0 , 0
9899.007    0.12       09899.007    0.12       010100.99    0.12       0
#XS Ineff= 2 , 0
       0                               0
Bank Sta=9899.007,10100.99
Exp/Cntr=0.3,0.1

Type RM Length L Ch R = 1 ,1796.661,24.852200,24.852200,24.852200
XS GIS Cut Line= 6
1156467.25168732848889.4708403261156485.68988917 848956.64340402
1156496.73985226848984.8647540961156497.66048664848986.640263133
1156508.06781369  849012.26743791156527.68044198849081.865810676
#Sta/Elev= 30
9899.035235.86139903.549233.57429906.336232.4912 9913.14230.33539930.151224.5482
9933.553223.50599936.955222.63449940.358221.9329 9943.76221.33899950.564220.4507
9968.692218.57679984.387217.27829992.199216.48059995.722216.35119999.257216.9276
10002.87217.993810006.41219.268510010.55220.982710017.04 223.87510028.66229.4003
10037.92233.325810039.83233.909110041.33 234.34710051.92236.753810078.83242.4918
10082.23243.283110088.21244.910210092.46245.944310095.87246.749910100.97247.7735
#Mann= 3 , 0 , 0
9899.035    0.12       09899.035    0.12       010100.97    0.12       0
#XS Ineff= 2 , 0
       0                               0
Bank Sta=9899.035,10100.97
Exp/Cntr=0.3,0.1

Type RM Length L Ch R = 1 ,1771.808,24.852200,24.852200,24.852200
XS GIS Cut Line= 4
1156449.60799091848898.9382366241156474.80533078848995.702626944
1156475.13412881848997.6754147821156500.58726652849094.374903137
#Sta/Elev= 29
9899.009231.76979910.061224.34489916.842220.06479921.688217.12439927.013214.0921
9930.403212.44359933.793211.44979957.525208.68799964.305207.74139974.476206.1824
9991.427203.36839994.817 202.9199998.208202.839310001.56203.351310004.95 204.726
10011.74208.041110018.52211.547710025.31215.151110032.09218.929610035.49220.7432
10038.88 222.15710042.27222.985310055.84225.744210066.02 228.05510069.41228.6874
 10072.8229.443910082.98232.313110086.37233.048710100.99234.7525
#Mann= 3 , 0 , 0
9899.009    0.12       09899.009    0.12       010100.99    0.12       0
#XS Ineff= 2 , 0
       0                               0
Bank Sta=9899.009,10100.99
Exp/Cntr=0.3,0.1

Type RM Length L Ch R = 1 ,1746.956,24.852200,24.852200,24.852200
XS GIS Cut Line= 6
1156432.25109773848899.8526259911156447.86730746848967.594207406
1156450.30129823848997.9093656381156451.02801257849018.794896631
1156454.52413038849044.2191785611156467.84616237849097.985600245
#Sta/Elev= 30
9899.069232.9829 9905.74227.92889912.474222.54249919.208217.01149925.942211.2094
9929.308208.43089932.675206.17189936.042 204.4129939.409202.95519943.357201.6736
9946.143201.0084 9949.51200.38449968.587197.92069989.434193.80579996.017192.7066
9999.307192.322810002.59192.271510005.87192.741410009.16 193.48210012.44194.5219
10019.01197.748510025.62200.638110032.24203.158410035.56204.111510045.56205.8944
10052.25207.545110069.15212.105510075.91213.674210082.67214.727610100.96216.6073
#Mann= 3 , 0 , 0
9899.069    0.12       09899.069    0.12       010100.96    0.12       0
#XS Ineff= 2 , 0
       0                               0
Bank Sta=9899.069,10100.96
Exp/Cntr=0.3,0.1

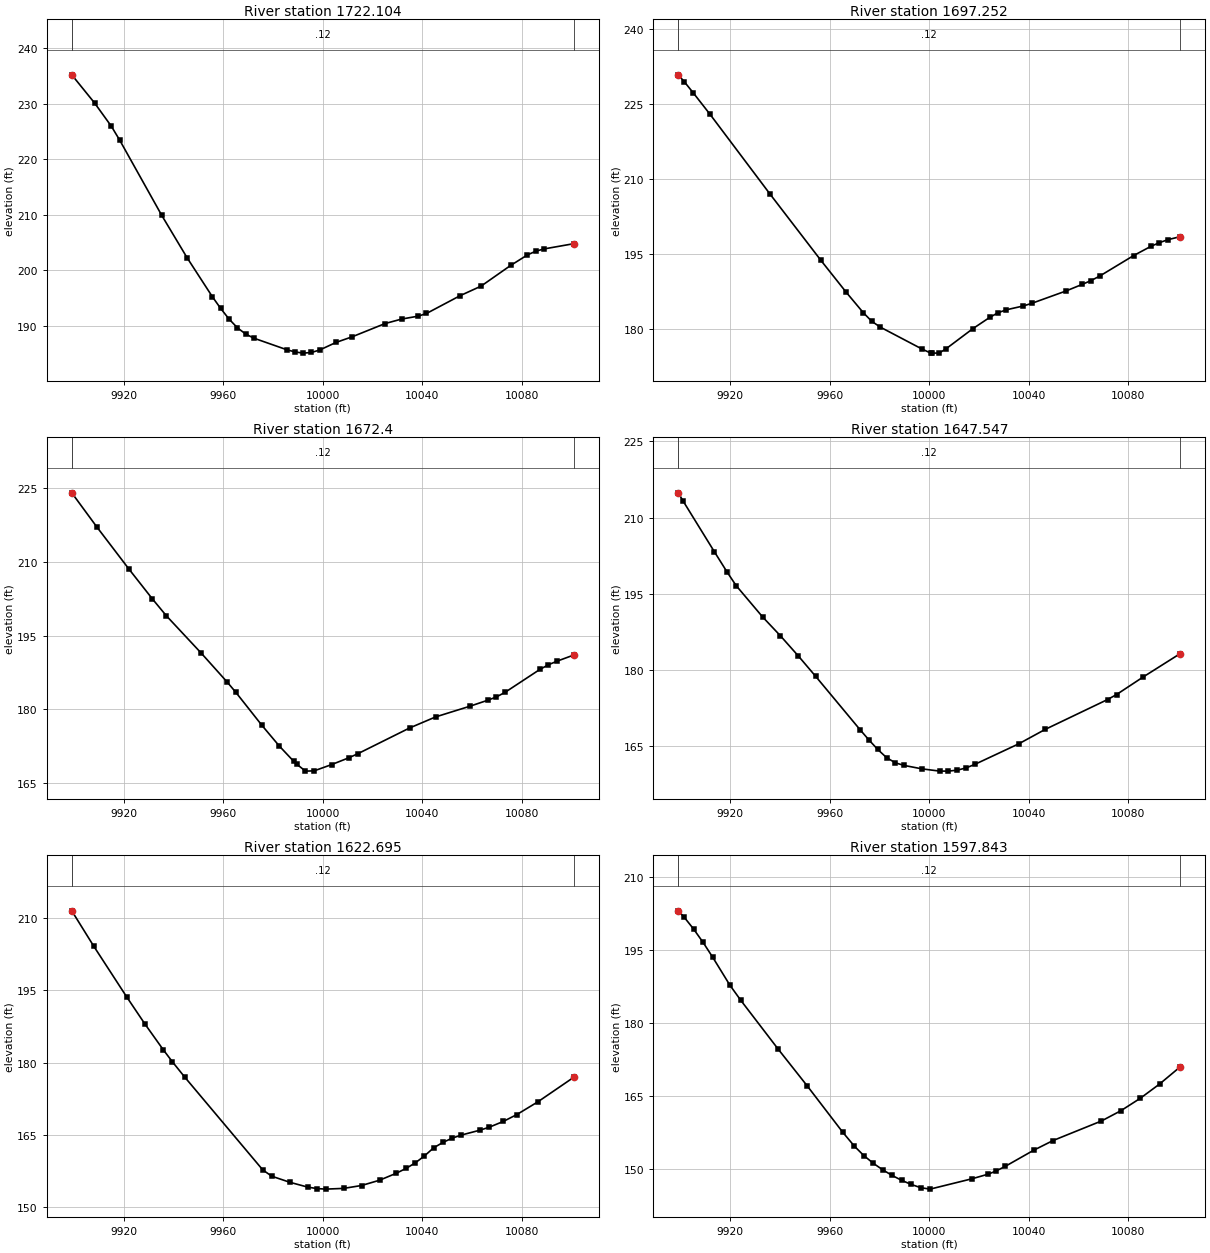
Type RM Length L Ch R = 1 ,1722.104,24.852200,24.852200,24.852200
XS GIS Cut Line= 6
1156405.62593168848900.7376053231156421.61356114848965.258350024
1156425.42570739848998.505098617 1156427.0071908849019.342434683
1156431.04410865849044.6906361851156445.11065696849098.263026927
#Sta/Elev= 30
9899.063235.19179908.229230.12499914.989225.92979918.369223.40969935.269209.8756
 9945.41202.2908 9955.55195.2895 9958.93193.1514 9962.31191.23479965.686189.6568
9968.989188.54339972.291187.7951  9985.5185.72019988.803185.32019992.105185.1044
9995.407185.2217 9998.71185.656110005.29187.023710011.87188.052210025.08190.4328
10031.73191.237610038.37191.7591 10041.7192.240910055.18195.433610063.66197.1647
10075.53200.882310082.32202.784310085.71203.4618 10089.1203.867110100.96204.8042
#Mann= 3 , 0 , 0
9899.063    0.12       09899.063    0.12       010100.96    0.12       0
#XS Ineff= 2 , 0
       0                               0
Bank Sta=9899.063,10100.96
Exp/Cntr=0.3,0.1

Type RM Length L Ch R = 1 ,1697.252,24.852200,24.852200,24.852200
XS GIS Cut Line= 6
1156373.07625104848907.2508659911156388.43015868848956.320598152
1156400.93506563849003.2606878861156401.44178447849005.195432318
1156414.73731104849057.4705230261156428.57634409849101.389592271
#Sta/Elev= 30
9899.007230.79979901.504229.37949904.942227.26019911.817222.88149935.881206.9623
9956.432193.63919966.618187.25269973.409183.21249976.804181.48549980.199180.3223
9997.175175.884610000.57 175.102   10001175.090510003.95175.104710006.63175.9143
 10017.5179.976410024.27182.227310027.65 183.17510031.04183.769710037.81184.5292
10041.19185.050510054.94187.519610061.61188.869210065.05189.609110068.49190.4931
10082.25 194.63110089.13196.458510092.57197.197510096.01197.803410100.99198.4081
#Mann= 3 , 0 , 0
9899.007    0.12       09899.007    0.12       010100.99    0.12       0
#XS Ineff= 2 , 0
       0                               0
Bank Sta=9899.007,10100.99
Exp/Cntr=0.3,0.1

Type RM Length L Ch R = 1 ,  1672.4,24.852200,24.852200,24.852200
XS GIS Cut Line= 4
1156342.35464092 848916.602297481156377.03297719  849010.3886389
1156377.78757102849012.2408235981156411.85577262849106.238577167
#Sta/Elev= 27
9899.008224.05239909.068217.12589922.022208.53549931.482202.44989937.052199.0497
9951.043191.47489961.537185.55889965.035183.46159975.529176.74379982.525172.5361
9988.243169.47119989.521168.86099993.018167.45019996.516167.506710003.53168.7785
10010.51170.1725   10014170.969410034.94 176.23410045.41178.481910059.37180.6821
10066.35181.869710069.84182.541610073.32183.479810087.28188.122710090.77189.0864
10094.26189.821910100.98191.0696
#Mann= 3 , 0 , 0
9899.008    0.12       09899.008    0.12       010100.98    0.12       0
#XS Ineff= 2 , 0
       0                               0
Bank Sta=9899.008,10100.98
Exp/Cntr=0.3,0.1

Type RM Length L Ch R = 1 ,1647.547,24.852200,24.852200,24.852200
XS GIS Cut Line= 5
1156315.15381137848927.5436517411156353.99689969849019.679917646
1156354.72820449849021.5414206131156375.04144124849071.509410015
1156394.08205922 849113.44373932
#Sta/Elev= 27
9899.011214.88459900.937213.29239913.568203.2679 9918.74199.2254  9922.3196.6117
9932.982 190.4239940.103186.73269947.224182.80679954.345178.71099972.147168.2326
9975.707166.21979979.268164.34359982.828162.72239986.389161.69719989.949161.1863
 9997.07160.514310004.15160.0762 10007.7160.069710011.24160.260810014.78160.6942
10018.32161.399210036.03165.456810046.65168.292510071.73174.170610075.33  175.15
10086.14178.641610100.99183.2317
#Mann= 3 , 0 , 0
9899.011    0.12       09899.011    0.12       010100.99    0.12       0
#XS Ineff= 2 , 0
       0                               0
Bank Sta=9899.011,10100.99
Exp/Cntr=0.3,0.1

Type RM Length L Ch R = 1 ,1622.695,24.852200,24.852200,24.852200
XS GIS Cut Line= 6
1156287.30148954 848939.145980071156314.28813058848992.786932996
1156330.94988647849029.0949969781156331.77305997849030.917738154
1156348.77905848849067.7002698371156376.84155171849120.126654216
#Sta/Elev= 30
9899.005211.5253 9907.86204.16949921.058193.68179928.403188.04689935.748182.7219
9939.421 180.218 9944.36177.05179975.855157.71719979.465156.41459986.684 155.162
9993.904154.15289997.514153.856610001.12153.732510008.35153.884310015.58154.4854
10022.81155.5788 10029.6157.037610033.65158.079410037.26159.208310040.88 160.617
10044.58162.3084 10048.3163.424410052.02164.317110055.74 164.96210063.19165.9709
10066.91166.581810072.63167.793210078.07  169.2210086.54171.869110100.99176.9704
#Mann= 3 , 0 , 0
9899.005    0.12       09899.005    0.12       010100.99    0.12       0
#XS Ineff= 2 , 0
       0                               0
Bank Sta=9899.005,10100.99
Exp/Cntr=0.3,0.1

Type RM Length L Ch R = 1 ,1597.843,24.852200,24.852200,24.852200
XS GIS Cut Line= 5
1156257.79923017848953.5016502221156308.38239974 849039.75463711
1156309.43510901849041.4551673741156329.66328291849076.569757851
1156361.78301502849126.618573206
#Sta/Elev= 30
9899.009203.08389901.402201.77199905.205199.32719909.009196.58499912.812193.5872
9919.797187.78229924.222184.64199939.253174.60489950.846167.10589965.195 157.532
9969.863154.67449973.666152.7353 9977.47151.15199981.273149.80559985.077148.6423
 9988.88147.64259992.683146.81279996.487146.137410000.31145.832910017.21147.9673
10023.79148.925610026.83 149.55410030.61150.528610041.98153.826210049.78155.8252
10069.27159.852110077.07161.957910084.87164.512410092.66167.456810100.99171.0068
#Mann= 3 , 0 , 0
9899.009    0.12       09899.009    0.12       010100.99    0.12       0
#XS Ineff= 2 , 0
       0                               0
Bank Sta=9899.009,10100.99
Exp/Cntr=0.3,0.1

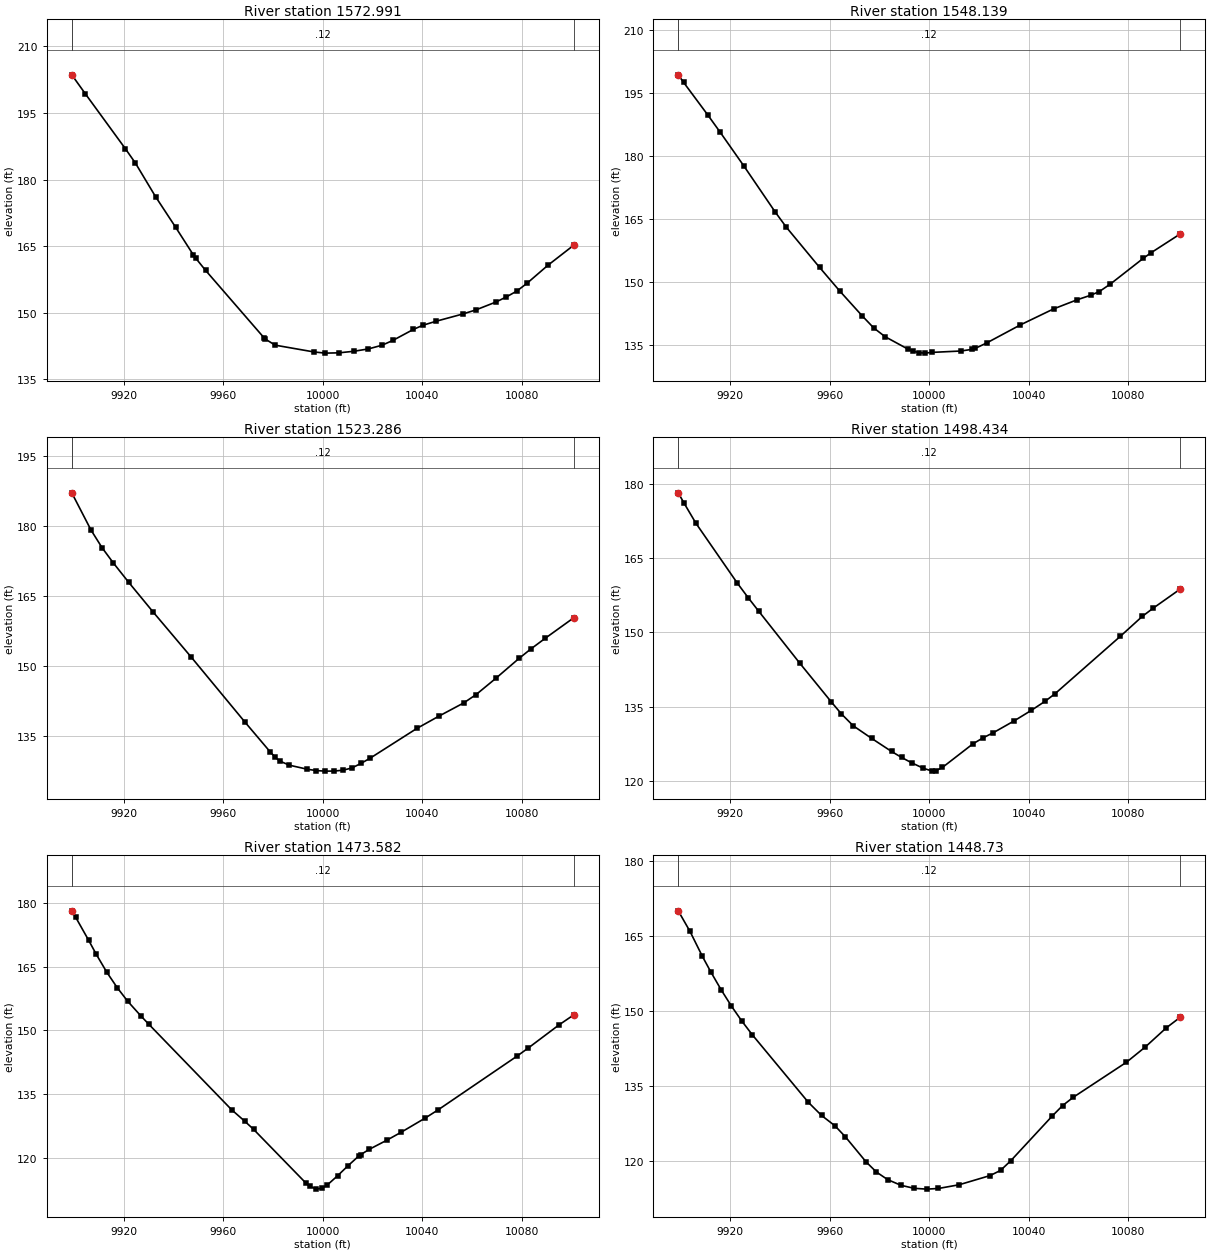
Type RM Length L Ch R = 1 ,1572.991,24.852200,24.852200,24.852200
XS GIS Cut Line= 6
1156230.03722702848970.8257016551156272.31670536849029.891499373
1156287.24326667849052.8174007941156288.29146157849054.520717397
1156300.90778549849073.5961143591156348.29641319849134.437841764
#Sta/Elev= 30
9899.005203.61099904.447199.35129920.586186.9522 9924.62 183.719 9932.69176.1815
9940.759169.29529947.859163.09429948.829162.33249952.863159.54099976.336144.3784
9976.911144.06469980.826142.70899996.485141.1745   10001140.913910006.42140.9786
10012.37141.322710018.31 141.85910023.87142.703610028.13143.761610036.45146.2602
10040.24147.188810045.58148.099110056.26149.7179 10061.6150.655410069.72152.4407
10073.87153.587110078.03154.885610082.19156.666210090.51160.685910100.99165.2429
#Mann= 3 , 0 , 0
9899.005    0.12       09899.005    0.12       010100.99    0.12       0
#XS Ineff= 2 , 0
       0                               0
Bank Sta=9899.005,10100.99
Exp/Cntr=0.3,0.1

Type RM Length L Ch R = 1 ,1548.139,24.852100,24.852100,24.852100
XS GIS Cut Line= 6
 1156197.9609203848995.6285120961156235.82027761849037.111848277
 1156267.2291796849067.6666172731156268.74769284849068.968199978
1156304.25274171849102.7809800681156338.58807891849140.423411295
#Sta/Elev= 30
9899.019199.2385 9901.18197.43599910.914189.67829915.781185.66879925.515 177.461
9938.057166.56039942.498162.96899955.862153.41189963.898147.83779973.053141.8425
 9977.63139.00959982.207136.91469991.361133.97419993.503133.44059995.938133.1051
9998.208132.9957   10001133.168810012.58133.495710017.34133.900210018.53134.1365
10023.06135.407810036.65139.715310050.03143.528810059.48145.696610064.86146.7573
10068.36147.6363 10072.8149.420910086.13155.5829 10089.2156.882210100.98161.3788
#Mann= 3 , 0 , 0
9899.019    0.12       09899.019    0.12       010100.98    0.12       0
#XS Ineff= 2 , 0
       0                               0
Bank Sta=9899.019,10100.98
Exp/Cntr=0.3,0.1

Type RM Length L Ch R = 1 ,1523.286,24.852200,24.852200,24.852200
XS GIS Cut Line= 6
1156174.05016509849028.5786831851156226.79524977849073.860399295
1156242.70944177849083.6009776361156269.49436517849095.572782677
1156287.15153602849107.3035737041156332.89578548849150.736431376
#Sta/Elev= 29
 9899.04 187.1389906.785179.15379911.256175.34999915.728172.13049921.956167.9455
9931.614161.69059947.156151.88319968.609138.05759978.823131.63019980.824 130.488
 9982.67129.66419986.516128.77699993.743127.90529997.331127.621210000.88127.4997
10004.48127.512210008.09127.6951 10011.7128.180610015.31129.142410019.13130.3074
10037.81136.6469 10046.6 139.25710056.64142.109110061.67143.914710069.52147.3607
10078.92151.659710083.62  153.6610089.55156.009110100.95160.3787
#Mann= 3 , 0 , 0
 9899.04    0.12       0 9899.04    0.12       010100.95    0.12       0
#XS Ineff= 2 , 0
       0                               0
Bank Sta=9899.04,10100.95
Exp/Cntr=0.3,0.1

Type RM Length L Ch R = 1 ,1498.434,24.852200,24.852200,24.852200
XS GIS Cut Line= 6
1156164.79658963849049.3774040521156202.27350581849080.845896134
1156243.72824768849110.6057097561156245.20010974849111.959822776
1156283.93848714849141.0425150611156322.37744419849175.347473937
#Sta/Elev= 29
9899.033178.2435  9901.4176.13359906.207 172.039 9922.82159.95549927.104157.0617
9931.388154.29559947.969143.73359960.609135.92089964.648133.51049969.429131.0963
9976.764128.57099984.841125.9004 9988.88124.69049992.919123.60739997.558122.5192
10001.19121.926810002.81122.052910005.29122.6747 10017.6127.4664 10021.7128.6805
 10025.8129.715810034.01132.057510041.06134.230910046.53136.049710050.49137.5535
10076.87149.221710085.67153.242510090.06154.904510100.96158.7781
#Mann= 3 , 0 , 0
9899.033    0.12       09899.033    0.12       010100.96    0.12       0
#XS Ineff= 2 , 0
       0                               0
Bank Sta=9899.033,10100.96
Exp/Cntr=0.3,0.1

Type RM Length L Ch R = 1 ,1473.582,24.852200,24.852200,24.852200
XS GIS Cut Line= 4
1156149.07259648849066.1311841791156226.90190869849128.895209685
1156228.37377075849130.2493227051156305.71869505849193.603228216
#Sta/Elev= 30
9899.016178.21759900.582 176.7059905.809171.27049908.901167.92979913.116163.7305
9917.331160.07129921.545156.87449926.714153.50299929.975151.49159963.299131.3258
9968.525128.64579972.122126.70839993.196114.02479994.657 113.2899997.411 112.595
9999.819112.855410001.74113.542310005.98115.763610010.09118.083510014.46   120.4
10015.27120.7383 10018.7121.983410025.63 124.09110031.43125.978110041.16129.3406
10046.34131.270110078.08143.935210082.58145.840710095.04151.331510100.98153.6984
#Mann= 3 , 0 , 0
9899.016    0.12       09899.016    0.12       010100.98    0.12       0
#XS Ineff= 2 , 0
       0                               0
Bank Sta=9899.016,10100.98
Exp/Cntr=0.3,0.1

Type RM Length L Ch R = 1 , 1448.73,24.852200,24.852200,24.852200
XS GIS Cut Line= 4
1156133.35602899849087.3616596041156212.09038357849148.985927283
1156213.70168563849150.1707081391156292.52258425849211.673021223
#Sta/Elev= 30
9899.017169.94999903.749165.8349 9908.75160.82419912.081157.77039916.247154.1855
9920.414150.9007 9924.58147.92269928.746145.20779951.335 131.6739956.658129.0397
9962.076  126.969966.243124.77119974.575 119.7559978.741117.72519983.273116.2035
9988.596115.07549993.919114.4684    9999 114.30710003.69114.438710012.01115.1801
 10024.5117.024310028.66118.049110032.82120.000510049.47128.929510053.63131.0121
10057.98132.691910079.31139.672910086.92 142.73710095.31  146.5410100.98148.6801
#Mann= 3 , 0 , 0
9899.017    0.12       09899.017    0.12       010100.98    0.12       0
#XS Ineff= 2 , 0
       0                               0
Bank Sta=9899.017,10100.98
Exp/Cntr=0.3,0.1

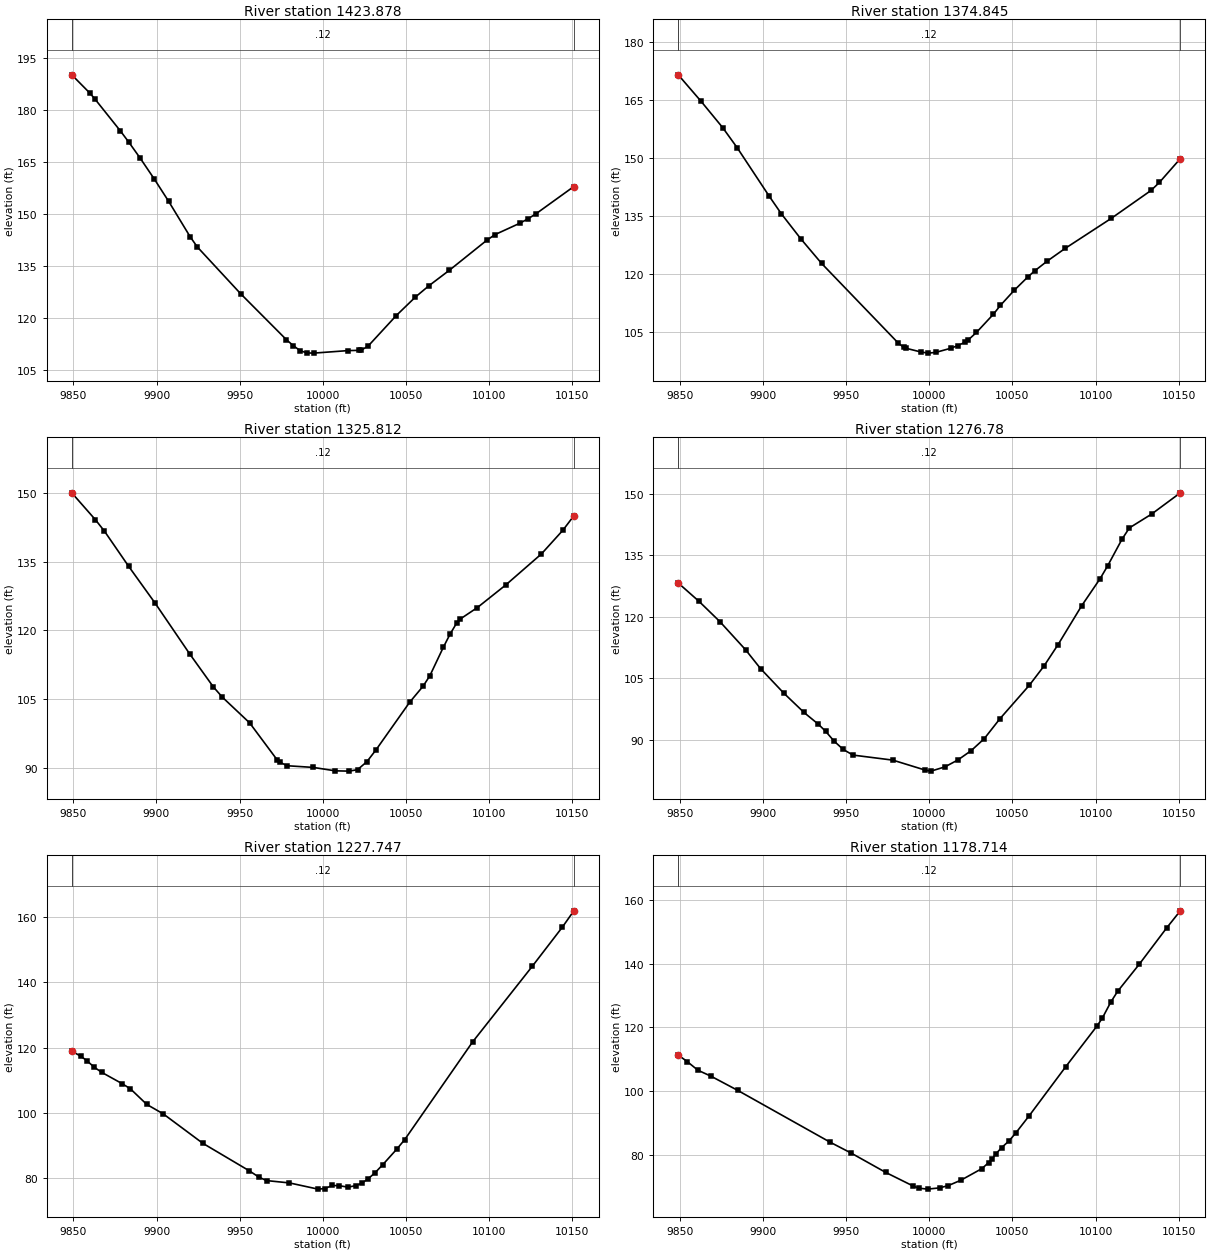
Type RM Length L Ch R = 1 ,1423.878,49.032700,49.032700,49.032700
XS GIS Cut Line= 6
1156079.55912536 849074.395974631156144.50922071849129.549781987
1156196.47554702849168.1827695471156197.98070044849169.499778722
1156267.97286892849220.9064161741156315.50178265849262.425526037
#Sta/Elev= 30
9849.038190.16889859.941184.87519863.132183.07869878.337173.92599883.406170.6738
 9890.07166.17649898.678160.05859907.286153.63329920.199143.41649924.503140.4628
9950.576126.94239978.138113.64669982.226111.95419986.314110.50659990.402109.8443
 9994.49 109.782   10015110.505910022.02 110.59110023.14110.663910027.21111.7994
10044.19120.6462 10055.7125.991610063.84129.261610076.06133.703510098.43142.3177
10103.42143.988910118.38147.279410123.37148.574810128.36150.090610150.95157.9058
#Mann= 3 , 0 , 0
9849.038    0.12       09849.038    0.12       010150.95    0.12       0
#XS Ineff= 2 , 0
       0                               0
Bank Sta=9849.038,10150.95
Exp/Cntr=0.3,0.1

Type RM Length L Ch R = 1 ,1374.845,49.032700,49.032700,49.032700
XS GIS Cut Line= 6
1156054.57149135849112.0894865681156095.96728226849147.944031741
1156155.91844025849195.169114089 1156187.8269529849225.107401769
1156252.62989784849275.7346248471156286.66195566849304.991889399
#Sta/Elev= 30
9849.022  171.549862.691164.72369875.712 157.9089884.393152.73619903.786140.1175
9911.013135.60989922.713129.13779935.243122.7596 9981.27102.19179984.738101.0139
9985.778100.84019994.79599.870219999.31899.5576710003.8899.7459310012.83100.8052
 10017.3101.526710021.77102.446310023.11102.841110028.36104.905510038.57109.6196
10042.73111.880210051.06115.793810059.39119.309310063.55120.884610070.99123.3774
10081.65126.622410109.47134.418210133.33141.621510138.37143.695810150.98149.8583
#Mann= 3 , 0 , 0
9849.022    0.12       09849.022    0.12       010150.98    0.12       0
#XS Ineff= 2 , 0
       0                               0
Bank Sta=9849.022,10150.98
Exp/Cntr=0.3,0.1

Type RM Length L Ch R = 1 ,1325.812,49.032700,49.032700,49.032700
XS GIS Cut Line= 6
1156023.89273236849152.8585355641156077.24237509849199.707957254
1156140.35584886849247.1398144461156151.89335599849256.578986388
1156211.80192219 849299.742491651156260.28890106849340.316198248
#Sta/Elev= 30
 9849.05149.97119863.295144.09579868.699141.62169883.184133.99539899.263125.8888
 9920.05114.83229934.168107.70089939.629105.44249956.012 99.85169972.39591.87273
9974.38591.258759978.48990.519399994.23890.1522710007.5289.4055610015.87 89.3431
10020.9389.6651110026.5491.4108710032.0594.0006310052.27104.361610060.35107.8612
 10064.4110.134810072.48116.316510076.53119.189510080.57121.640210082.67 122.482
10092.99 124.984 10110.1129.920310131.49136.666910144.32141.795910150.97144.9641
#Mann= 3 , 0 , 0
 9849.05    0.12       0 9849.05    0.12       010150.97    0.12       0
#XS Ineff= 2 , 0
       0                               0
Bank Sta=9849.05,10150.97
Exp/Cntr=0.3,0.1

Type RM Length L Ch R = 1 , 1276.78,49.032700,49.032700,49.032700
XS GIS Cut Line= 6
1156000.24671621849193.7045783561156031.90725604849225.513454603
1156066.36733793849255.6297935671156166.23129187849322.960383608
1156201.69229764849351.5083644311156235.16298426849382.028681805
#Sta/Elev= 30
9849.029128.2908 9861.62123.78089874.095118.86289889.525112.00699898.516107.4179
9912.454101.44939924.65996.715989933.37393.81625 9937.7392.095749942.68189.75277
9948.245 87.6942 9954.1186.318599978.092 85.08819997.60482.65073   1000182.40567
10009.4183.4418510017.2885.1468810025.16 87.393210033.0390.3019110042.4595.16413
10060.24103.383810069.05108.076310077.48113.283810091.63122.730810102.75 129.359
10107.21132.429410115.91138.974910120.35141.732410133.67145.090110150.97150.2853
#Mann= 3 , 0 , 0
9849.029    0.12       09849.029    0.12       010150.97    0.12       0
#XS Ineff= 2 , 0
       0                               0
Bank Sta=9849.029,10150.97
Exp/Cntr=0.3,0.1

Type RM Length L Ch R = 1 ,1227.747,49.032700,49.032700,49.032700
XS GIS Cut Line= 6
 1155985.6782119849217.714911915 1156027.6645246849264.848928579
1156076.54087644849314.5104084361156088.69572736  849329.3446902
1156103.30364752849346.9327853251156190.26108487849439.651828207
#Sta/Elev= 30
9849.019 118.9219854.681117.28639858.232115.92559862.625113.96179867.019112.4284
9879.343108.95159884.276107.38689894.141102.60229904.00699.724669927.81390.71673
9955.87682.259559961.53680.360129966.13979.298939979.94978.579429997.118 76.6818
10001.3176.8532910005.5777.7969210009.8477.7377810015.1177.2904110020.2577.78396
10023.8678.6587510027.0679.7499610031.5681.7658910036.0684.1661110044.4788.91262
10049.2691.8385410090.03  121.6910126.02144.908410144.01156.820110150.98161.8579
#Mann= 3 , 0 , 0
9849.019    0.12       09849.019    0.12       010150.98    0.12       0
#XS Ineff= 2 , 0
       0                               0
Bank Sta=9849.019,10150.98
Exp/Cntr=0.3,0.1

Type RM Length L Ch R = 1 ,1178.714,45.067600,45.067600,45.067600
XS GIS Cut Line= 6
 1155963.3690783849237.8723161131156034.83301016849340.215960915
1156050.51498609849359.8889176451156051.77338259 849361.44340735
1156070.77607565849385.0432503111156141.95287741 849481.27621224
#Sta/Elev= 30
9849.016111.34689854.448109.29819860.832106.60329868.835104.69679884.841100.2697
9940.40784.038849952.86780.682769973.84274.571539990.50370.265889993.80669.64671
    9999 69.346210006.2469.7404110011.4770.4601610019.06 72.148810031.6975.78784
10035.7777.6887710037.9878.8808510039.8580.2846110043.4982.3350110048.0184.47367
10052.0986.9757710060.0592.3010510082.11107.722110101.06 120.57110104.18123.0203
10109.22127.9883 10113.3131.318910126.25139.7704 10142.8   151.210150.99156.5386
#Mann= 3 , 0 , 0
9849.016    0.12       09849.016    0.12       010150.99    0.12       0
#XS Ineff= 2 , 0
       0                               0
Bank Sta=9849.016,10150.99
Exp/Cntr=0.3,0.1

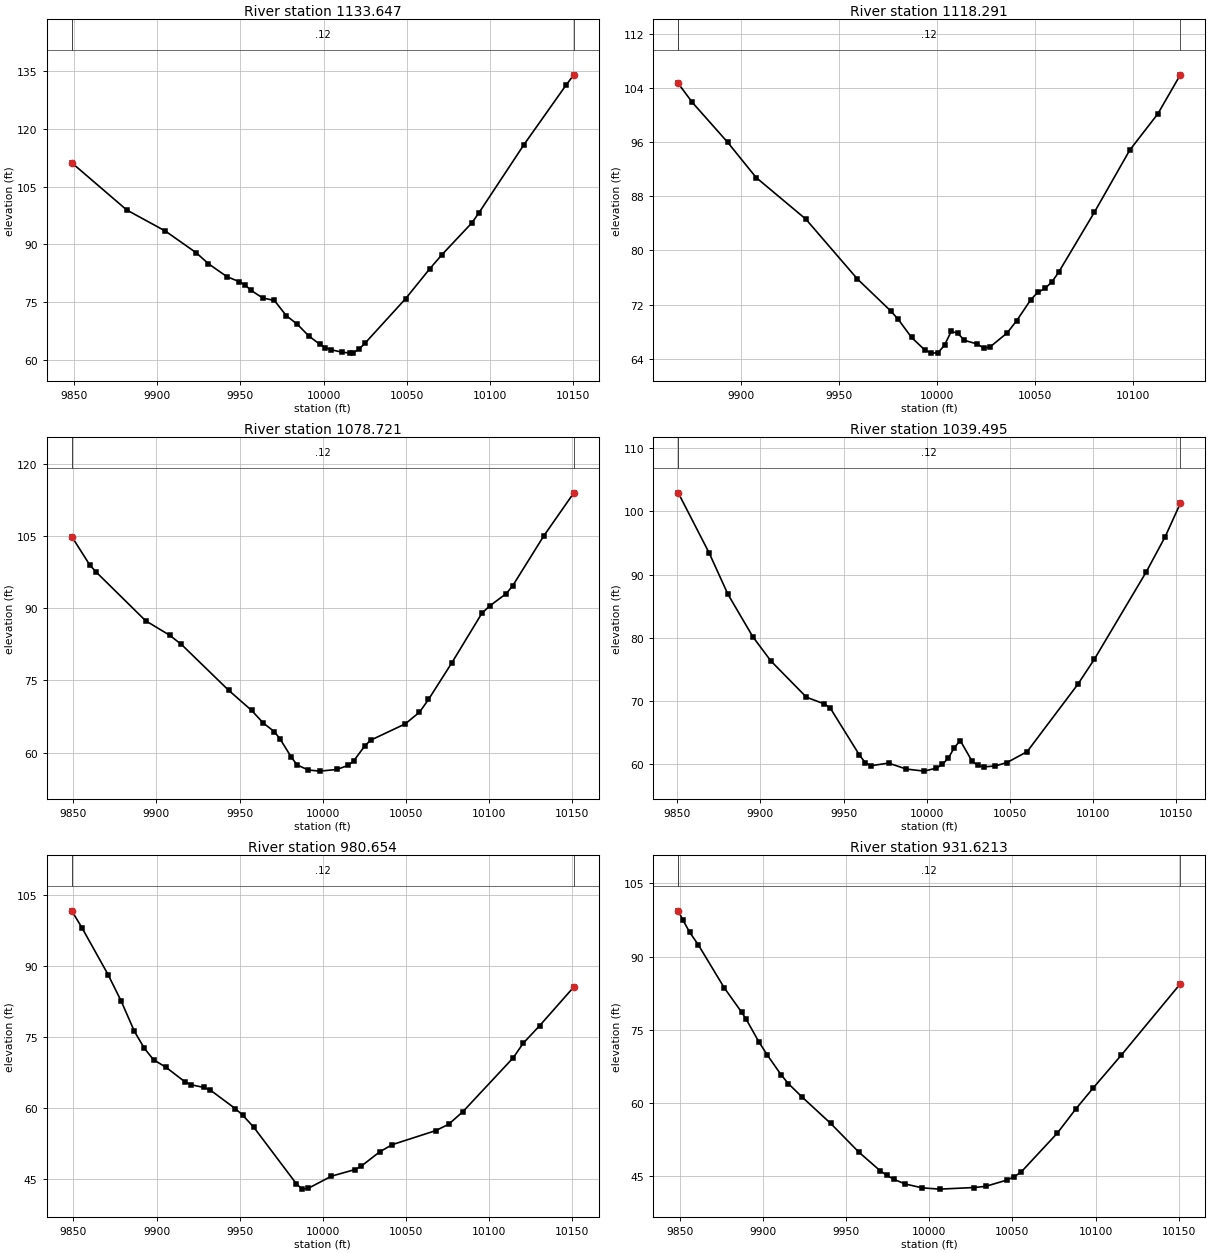
Type RM Length L Ch R = 1 ,1133.647,15.355200,15.355200,15.355200
XS GIS Cut Line= 6
1155946.07709249849242.4642204941155994.75494698849326.327509024
1156007.09527388849356.4085231961156015.06862186849393.500699541
1156027.13491596849426.831469523  1156073.462319849514.108024355
#Sta/Elev= 30
 9848.59111.18339881.65298.907629904.84293.425769923.36487.788979930.773  84.916
9941.88781.551999949.13980.277689952.68579.439339956.23178.033389963.32476.02171
9970.41675.360379977.50871.434799984.27469.142439991.00966.154579997.74363.95312
10001.06 63.112810004.4162.5453410011.1361.91137 10016.161.6628810017.9161.75709
 10021.462.7390310024.8964.2500110049.3175.8402510063.7683.5781910071.0487.22949
10089.2295.5919510093.4998.2443110120.29115.809810145.72131.378610150.44134.0727
#Mann= 3 , 0 , 0
 9848.59    0.12       0 9848.59    0.12       010150.44    0.12       0
#XS Ineff= 2 , 0
       0                               0
Bank Sta=9848.59,10150.44
Exp/Cntr=0.3,0.1

Type RM Length L Ch R = 1 ,1118.291,39.570700,39.570700,39.570700
XS GIS Cut Line= 5
1155944.01935413849257.4718778581155992.63330057849361.075370297
1155999.80585003849391.3594680581155998.21195015849413.674066439
1156034.87164745849494.166010529
#Sta/Elev= 30
9868.005 104.6559875.176101.86349893.296 95.94349907.79390.756279933.161 84.6134
9959.49475.77341 9976.6571.007489980.27469.833889987.16867.127369993.91265.28393
9997.283 64.817710000.6564.8656410004.0366.01584 10007.468.0389410010.7767.74636
10014.13 66.713510020.7166.1587210023.9965.5637810027.28 65.741410035.9467.79582
10040.8769.6245610048.0872.7302810051.6973.8228410055.2974.36989 10058.975.36895
10062.2876.7758710080.5385.6403110098.5594.7984810112.97100.195610124.39105.9303
#Mann= 3 , 0 , 0
9868.005    0.12       09868.005    0.12       010124.39    0.12       0
#XS Ineff= 2 , 0
       0                               0
Bank Sta=9868.005,10124.39
Exp/Cntr=0.3,0.1

Type RM Length L Ch R = 1 ,1078.721,39.225200,39.225200,39.225200
XS GIS Cut Line= 6
1155905.42402139849257.8168396121155927.69851471849298.485764971
1155943.17436402849333.9240274251155971.49782223849429.887971762
1155984.32430757849465.5841272631156020.23104619849535.728810286
#Sta/Elev= 30
 9849.13104.8504 9859.8899.005519863.62197.548589893.54687.38039 9907.9584.38462
 9915.1182.451549943.44172.951799957.29968.76378 9964.1966.179689970.98164.34235
9974.37762.843019981.16959.060769984.56557.458869991.35756.402359998.14956.16497
10008.4256.5042810015.2557.3356610018.6658.2898510025.4861.46473 10028.962.59306
 10049.765.9781710058.2368.4029610063.6471.0344810077.7778.70718 10095.888.95671
10100.3490.4249510110.4393.0257910114.1894.5885510132.93104.972410151.05113.9361
#Mann= 3 , 0 , 0
 9849.13    0.12       0 9849.13    0.12       010151.05    0.12       0
#XS Ineff= 2 , 0
       0                               0
Bank Sta=9849.13,10151.05
Exp/Cntr=0.3,0.1

Type RM Length L Ch R = 1 ,1039.495,58.841500,58.841500,58.841500
XS GIS Cut Line= 6
 1155862.1484545849267.453974211 1155882.0564575849302.751380113
1155896.61643781849333.2772527151155954.33734219849478.697635449
1155971.06201018849511.3013684521155988.73534867849540.778432082
#Sta/Elev= 30
9850.617102.9506 9869.2193.41937 9880.5186.864619895.42280.157119906.32776.29822
9927.70570.554249938.53769.482799942.04268.834189959.56561.39007 9963.07 60.1793
9966.57559.695469977.089 60.11329987.67359.169849998.48158.8384710005.8359.31287
10009.4759.9054710013.1260.9425110016.6862.5824110020.1963.6854310027.2260.45032
10030.7459.7439510034.2559.5072610041.2859.65702 10048.360.1989110060.4361.92916
10090.9172.6079110100.9276.6089510131.9790.3839110143.44 96.003510152.52101.2741
#Mann= 3 , 0 , 0
9850.617    0.12       09850.617    0.12       010152.52    0.12       0
#XS Ineff= 2 , 0
       0                               0
Bank Sta=9850.617,10152.52
Exp/Cntr=0.3,0.1

Type RM Length L Ch R = 1 , 980.654,49.032700,49.032700,49.032700
XS GIS Cut Line= 6
1155794.90295823849288.3891707931155845.55667159849370.524151487
1155861.83383167849403.0649530861155874.39425046849435.362203436
1155894.86287845849473.9752929111155944.39487375 849549.86444358
#Sta/Elev= 30
9849.031101.75079855.13398.179759870.82988.270259878.67782.692689886.688 76.2384
9892.66972.652719898.18570.227959905.778 68.61039917.16765.522439920.96464.91614
9928.55764.347369932.35363.803639947.47359.84237 9951.8558.476819958.47855.93882
9984.06543.978649987.58142.831039991.09742.9727110005.1445.5681810019.4246.98086
10023.1447.7030210034.2850.73758 10041.752.2404910067.9755.2260810075.6856.56198
10084.2659.2318910114.5170.6386310120.5673.7330810130.4677.4541110150.9785.64043
#Mann= 3 , 0 , 0
9849.031    0.12       09849.031    0.12       010150.97    0.12       0
#XS Ineff= 2 , 0
       0                               0
Bank Sta=9849.031,10150.97
Exp/Cntr=0.3,0.1

Type RM Length L Ch R = 1 ,931.6213,49.032700,49.032700,49.032700
XS GIS Cut Line= 5
 1155735.6993269849334.0380690031155830.62311774 849450.17617663
1155831.91841462849451.7000552291155853.15218194849477.601106814
1155928.31781574 849566.61428109
#Sta/Elev= 30
9849.00599.361299851.72397.53052 9855.9694.935159861.14592.355779876.698 83.5855
9887.06678.629929889.85877.164349897.43572.566279902.61969.810499911.04565.69412
9915.28263.952399923.35661.269359940.70555.816899957.655 49.93189970.366  46.154
9974.604 45.15619978.84144.343679985.56743.40764 9995.7942.6166410006.2542.35902
10026.9542.68926   1003442.9320210046.8744.2361910051.1744.8998410055.4645.92917
10076.9353.79376 10088.158.75763 10098.462.9996410115.5869.83251   1015184.40828
#Mann= 3 , 0 , 0
9849.005    0.12       09849.005    0.12       0   10151    0.12       0
#XS Ineff= 2 , 0
       0                               0
Bank Sta=9849.005,10151
Exp/Cntr=0.3,0.1