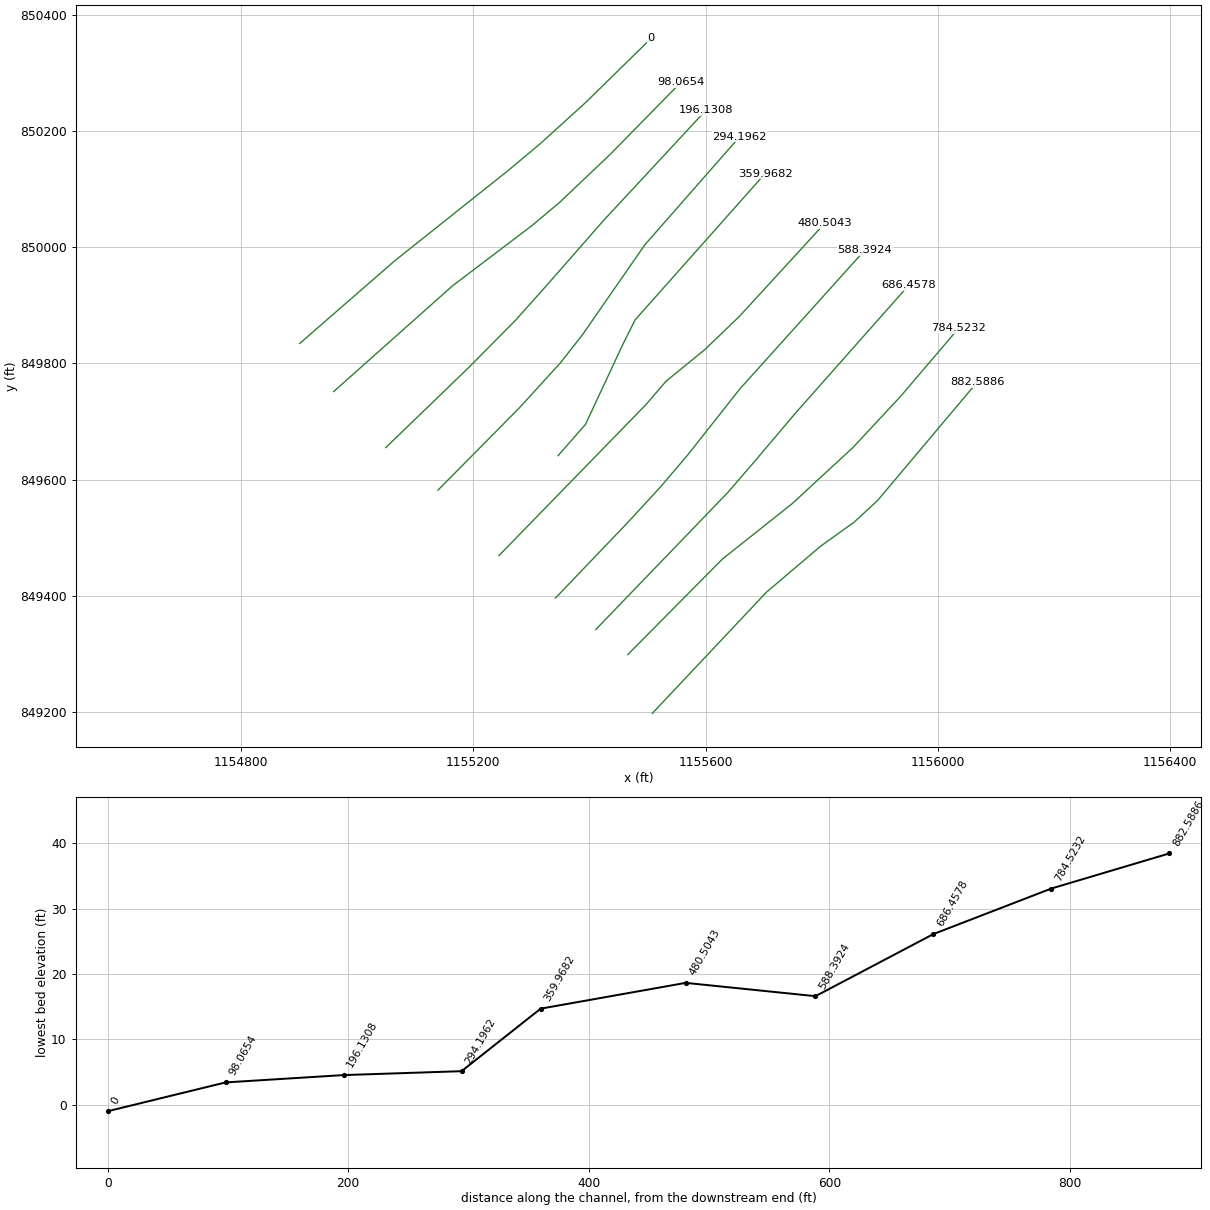
HEC-RAS study 167_ras.prj: 167

--- 167_ras.g01 (geometry) --- (continued)

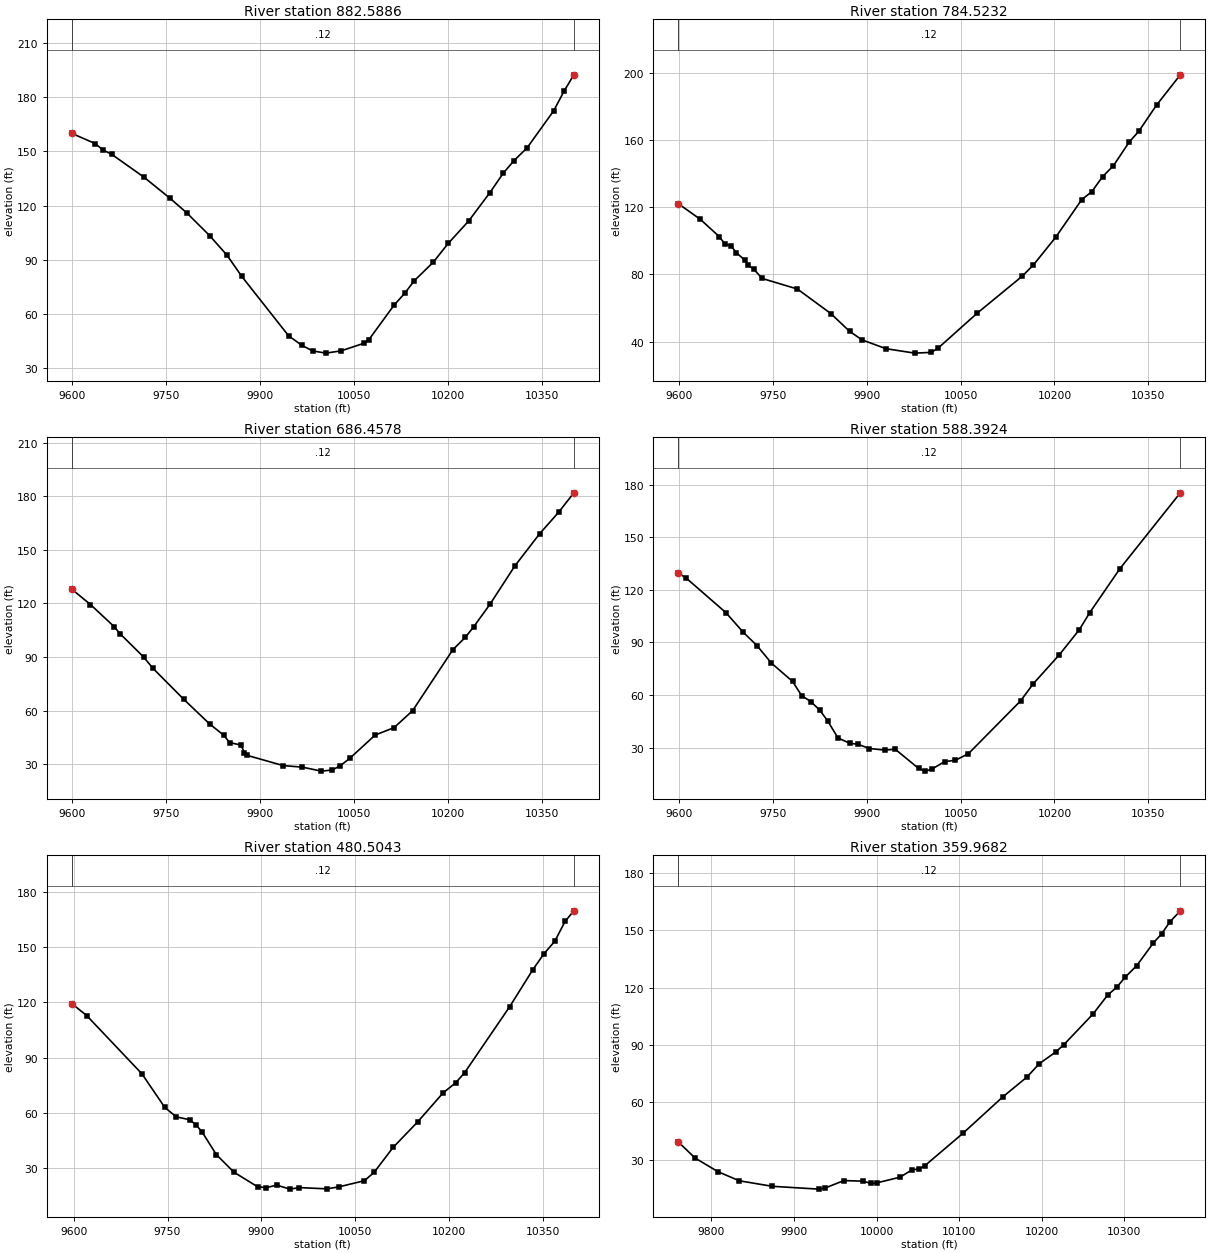
Type RM Length L Ch R = 1 ,882.5886,98.065400,98.065400,98.065400
XS GIS Cut Line= 6
1155508.35516835849197.3652769091155704.85736323849406.000935387
1155798.30424209 849485.293952891155855.73501094849526.520220077
1155896.05064618849563.6254496621156068.00084912849768.004288753
#Sta/Elev= 30
 9599.04159.86039636.203154.24399649.232150.61669662.558148.35069714.069135.7315
 9755.84124.04289782.666115.95299819.293 103.355 9847.2492.438169870.48380.88065
9945.51247.97892  9966.7 42.7631 9983.65 39.708410005.0738.4757810029.5339.76484
10065.8843.95129 10073.245.7412910113.5664.86458 10131.471.7703610145.9378.42286
10176.2588.6255210200.1699.0267410233.01111.490710266.91127.152810288.09 137.821
10305.04   144.710326.22151.842110368.59172.267310385.65183.387810400.92192.1885
#Mann= 3 , 0 , 0
 9599.04    0.12       0 9599.04    0.12       010400.92    0.12       0
#XS Ineff= 2 , 0
       0                               0
Bank Sta=9599.04,10400.92
Exp/Cntr=0.3,0.1

Type RM Length L Ch R = 1 ,784.5232,98.065400,98.065400,98.065400
XS GIS Cut Line= 6
1155466.18101346849298.616557487 1155629.1296683849463.110267241
1155749.79824833849558.9512218671155854.40151231849655.740478763
1155936.09565308849743.4512548571156035.81588705849860.469046714
#Sta/Elev= 30
9599.054122.17659634.516112.75859664.762102.44279673.865 97.99249682.96797.16835
9692.06992.872269705.52488.444039710.25885.561299719.37683.241139733.029 77.5983
9789.44971.27713 9842.8156.666169872.98545.996039892.84840.976389930.67335.75967
 9976.7833.1024510003.2333.5493610013.8736.0030710076.8657.0071510148.2378.86558
10166.4685.6832310202.39102.375610243.59124.5897 10259.5129.245610276.74138.2246
10294.05144.712710319.34158.887910334.52165.208410362.96180.860510400.95198.9021
#Mann= 3 , 0 , 0
9599.054    0.12       09599.054    0.12       010400.95    0.12       0
#XS Ineff= 2 , 0
       0                               0
Bank Sta=9599.054,10400.95
Exp/Cntr=0.3,0.1

Type RM Length L Ch R = 1 ,686.4578,98.065400,98.065400,98.065400
XS GIS Cut Line= 6
1155410.97928682849341.6680074881155638.66234361849578.039621391
1155685.56806693849632.3864903271155686.84826589849633.923074402
1155754.71788684849714.1860567951155950.21272122849934.947306192
#Sta/Elev= 30
9599.017127.95319628.889119.35839666.722 106.9869676.181103.01659714.01489.90448
9728.00483.922539778.11366.255699819.11152.568669841.70146.233749851.15942.10824
9869.219 40.71899874.80536.50466 9878.3335.030919936.84529.226069967.38328.35723
 9997.7226.13035 10014.926.7601510027.5829.0621910042.8333.2090310083.6546.31535
10113.8850.4732610143.4559.9724910207.7894.1019310227.58 100.97410240.97106.8664
10267.17119.5813 10306.7140.938810346.14158.877610376.82171.061210400.99181.8749
#Mann= 3 , 0 , 0
9599.017    0.12       09599.017    0.12       010400.99    0.12       0
#XS Ineff= 2 , 0
       0                               0
Bank Sta=9599.017,10400.99
Exp/Cntr=0.3,0.1

Type RM Length L Ch R = 1 ,588.3924,107.888100,107.888100,107.888100
XS GIS Cut Line= 6
 1155341.6176967849395.9350564191155465.94210943849525.937964627
1155521.15245349849585.7846183091155568.78096572849641.654580827
1155659.40838378849756.4020804011155874.21617428849994.958335624
#Sta/Elev= 30
9599.013129.65139611.612126.77859675.166107.03369702.40495.997599725.10288.10295
  9747.878.254459781.62367.789459796.13959.687319810.655 56.3182 9825.1751.35979
9837.59345.303369854.20135.552949872.85932.527549885.793 31.95949904.49729.51422
9928.905 28.61489945.68729.083729983.04418.128679993.82216.6167610003.7817.69041
10024.5122.0389710041.8322.8190410062.5426.5704310145.7756.6535210166.2466.52313
10207.5882.9280810239.7997.3331510256.15106.949810304.71132.204210400.99 175.382
#Mann= 3 , 0 , 0
9599.013    0.12       09599.013    0.12       010400.99    0.12       0
#XS Ineff= 2 , 0
       0                               0
Bank Sta=9599.013,10400.99
Exp/Cntr=0.3,0.1

Type RM Length L Ch R = 1 ,480.5043,120.536100,120.536100,120.536100
XS GIS Cut Line= 6
1155244.41030318849469.1678700961155498.07128128849729.740061551
 1155532.2716065849769.5868784811155598.50660423849823.537619834
1155657.91142129849880.5508118421155805.26197992850041.148771185
#Sta/Elev= 30
9597.099119.29569621.025 112.7649709.06581.232279745.69462.966179764.00957.84148
9785.64556.28328 9796.0653.331969805.21749.682339827.97637.395799856.19627.81329
9893.82419.958679907.93419.435839924.26320.839389945.56118.653579960.74919.48919
10004.1218.8072810023.1919.8325110064.6223.23463 10080.227.8417210110.2641.26352
10149.4355.0785510190.3270.9225810210.0476.2635410224.4281.7620710296.66117.6989
 10333.3137.579110350.95 146.186 10368.6153.136110384.96 163.85710398.99  169.61
#Mann= 3 , 0 , 0
9597.099    0.12       09597.099    0.12       010398.99    0.12       0
#XS Ineff= 2 , 0
       09974.222                       0
Bank Sta=9597.099,10398.99
Exp/Cntr=0.3,0.1

Type RM Length L Ch R = 1 ,359.9682,65.772000,65.772000,65.772000
XS GIS Cut Line= 5
1155346.11159268849641.0957913991155393.34660602849695.078663781
1155457.45126697849832.2851310221155478.81948724849875.021571666
1155702.62347895850126.941642702
#Sta/Elev= 30
9759.82439.399079780.19330.964519807.99623.810919833.71319.069619873.54716.18756
 9929.9214.70668 9937.6715.299029960.45719.183549984.11218.839789993.17817.66862
10000.5118.0048910028.1320.9108810042.8424.7485910051.6225.3060210058.6327.02202
10104.28 43.778910152.49 62.782410182.13 73.299210196.9580.2409310216.7186.29585
10226.5990.1219210262.27106.314910279.82116.132210290.81120.196310300.69125.3251
10314.93131.466410335.26143.421810345.14 148.10410355.02 154.27910367.75160.1305
#Mann= 3 , 0 , 0
9759.824    0.12       09759.824    0.12       010367.75    0.12       0
#XS Ineff= 2 , 0
       09958.101                       0
Bank Sta=9759.824,10367.75
Exp/Cntr=0.3,0.1

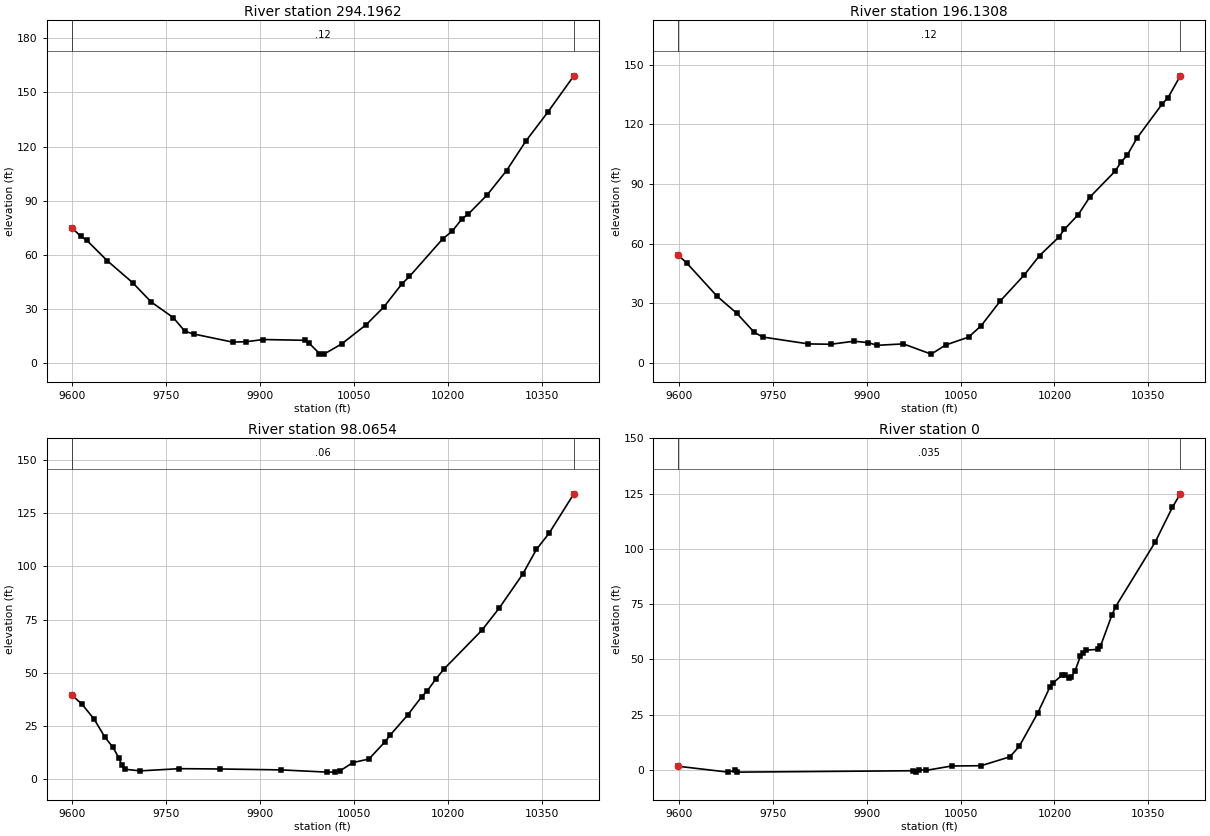
Type RM Length L Ch R = 1 ,294.1962,98.065400,98.065400,98.065400
XS GIS Cut Line= 6
1155139.27861865849581.7840719381155278.39773653849722.369664263
1155350.30538325849801.1131043761155388.53695736849849.985018369
1155495.73179435 850004.503226211155658.83952313850190.373388583
#Sta/Elev= 30
9599.04475.109639613.48370.291939622.97768.130889655.62756.855489696.56544.57745
9725.59234.097729761.18425.320749779.64717.815439793.49416.29244 9855.8211.79811
9878.03512.007219904.61613.216529970.96812.787269978.20811.153569994.6795.462038
10001.865.13280310030.0110.7560610069.2721.4137210097.4731.2183710126.1443.93599
10138.43 48.118710191.7969.0316810206.3273.0281610222.3680.0024310232.5582.69334
10262.5693.2801810293.44106.672310324.33123.059710359.63139.165110400.97159.1538
#Mann= 3 , 0 , 0
9599.044    0.12       09599.044    0.12       010400.97    0.12       0
#XS Ineff= 2 , 0
       09969.619                       0
Bank Sta=9599.044,10400.97
Exp/Cntr=0.3,0.1

Type RM Length L Ch R = 1 ,196.1308,98.065400,98.065400,98.065400
XS GIS Cut Line= 6
1155049.32948412849654.9474614831155192.53851869849793.218865139
1155273.32143358849874.8060643321155330.62519754849939.061205989
1155424.12239031850045.7967477581155601.12415506850236.365656973
#Sta/Elev= 30
9599.02354.225319612.38150.398859660.80733.689879692.73125.009419720.09415.59117
9733.77513.136579806.9389.6658799842.7969.4982339879.73111.027149902.81610.29096
9916.4878.9629329958.6229.67691210003.084.53700210026.149.103864 10062.813.10021
10082.7118.73085 10113.431.2213810152.0344.4154410176.1454.04561 10206.763.23885
10215.6667.1771610238.0574.6525310255.9683.2431510296.6696.38321 10306.3100.9645
10315.95104.391810332.08113.200710372.38130.368610381.33133.356210400.98144.3518
#Mann= 3 , 0 , 0
9599.023    0.12       09599.023    0.12       010400.98    0.12       0
#XS Ineff= 2 , 0
       09963.292                       0
Bank Sta=9599.023,10400.98
Exp/Cntr=0.3,0.1

Type RM Length L Ch R = 1 , 98.0654,98.065400,98.065400,98.065400
XS GIS Cut Line= 6
1154959.78739769849751.6116978371155164.11804152849933.406492953
 1155301.9279535850037.9784937871155348.31831407850076.853153309
1155435.40075116850159.5453467451155557.83498716  850284.2741681
#Sta/Elev= 30
9599.01739.607889615.44835.268889634.98128.183089651.46320.000329664.751 15.0539
9674.04810.178519678.9316.6294079683.8144.7662829708.2314.0004689770.7155.037446
 9835.874.8907629933.745  4.459210007.18 3.4132510019.383.44688410027.514.012408
10047.957.88841210073.639.55449610099.3217.63806 10107.220.6415210135.7930.29239
10157.7538.74893 10166.841.5499810180.3747.0341610193.9451.9126510253.8969.94575
10281.7980.3956910319.2696.3161210341.24107.961510361.41115.513310400.97134.0272
#Mann= 3 , 0 , 0
9599.017    0.06       09599.017    0.06       010400.97    0.06       0
#XS Ineff= 2 , 0
       09951.072                       0
Bank Sta=9599.017,10400.97
Exp/Cntr=0.3,0.1

Type RM Length L Ch R = 1 ,       0,0.000000,0.000000,0.000000
XS GIS Cut Line= 6
1154901.26352536849834.3845676451155064.73836246849976.643749186
1155259.57729128850131.7318219491155315.55022105850178.464274109
1155393.63569795850249.3392590961155506.40482285850359.784140899
#Sta/Elev= 30
9599.0171.6469639678.793  -0.9999689.703-0.199659693.625  -0.9999974.517-0.36717
9978.712  -0.9999982.9070.0888979995.492  -0.17810035.831.778547 10082.7 1.89904
10128.775.925693 10143.910.7403510173.1225.6836210192.6437.4523410197.0739.24667
10212.1742.8384910217.0542.9164810223.6541.3768510226.8241.9825110232.5144.55338
10241.3851.4421310246.2252.97709 10250.554.1685610268.8754.5362510273.4655.95055
10291.8370.1539610297.7973.9153310360.71102.987410388.26118.746810400.98124.9011
#Mann= 3 , 0 , 0
9599.017   0.035       09599.017   0.035       010400.98   0.035       0
#XS Ineff= 2 , 0
       09970.223                       0
Bank Sta=9599.017,10400.98
Exp/Cntr=0.3,0.1